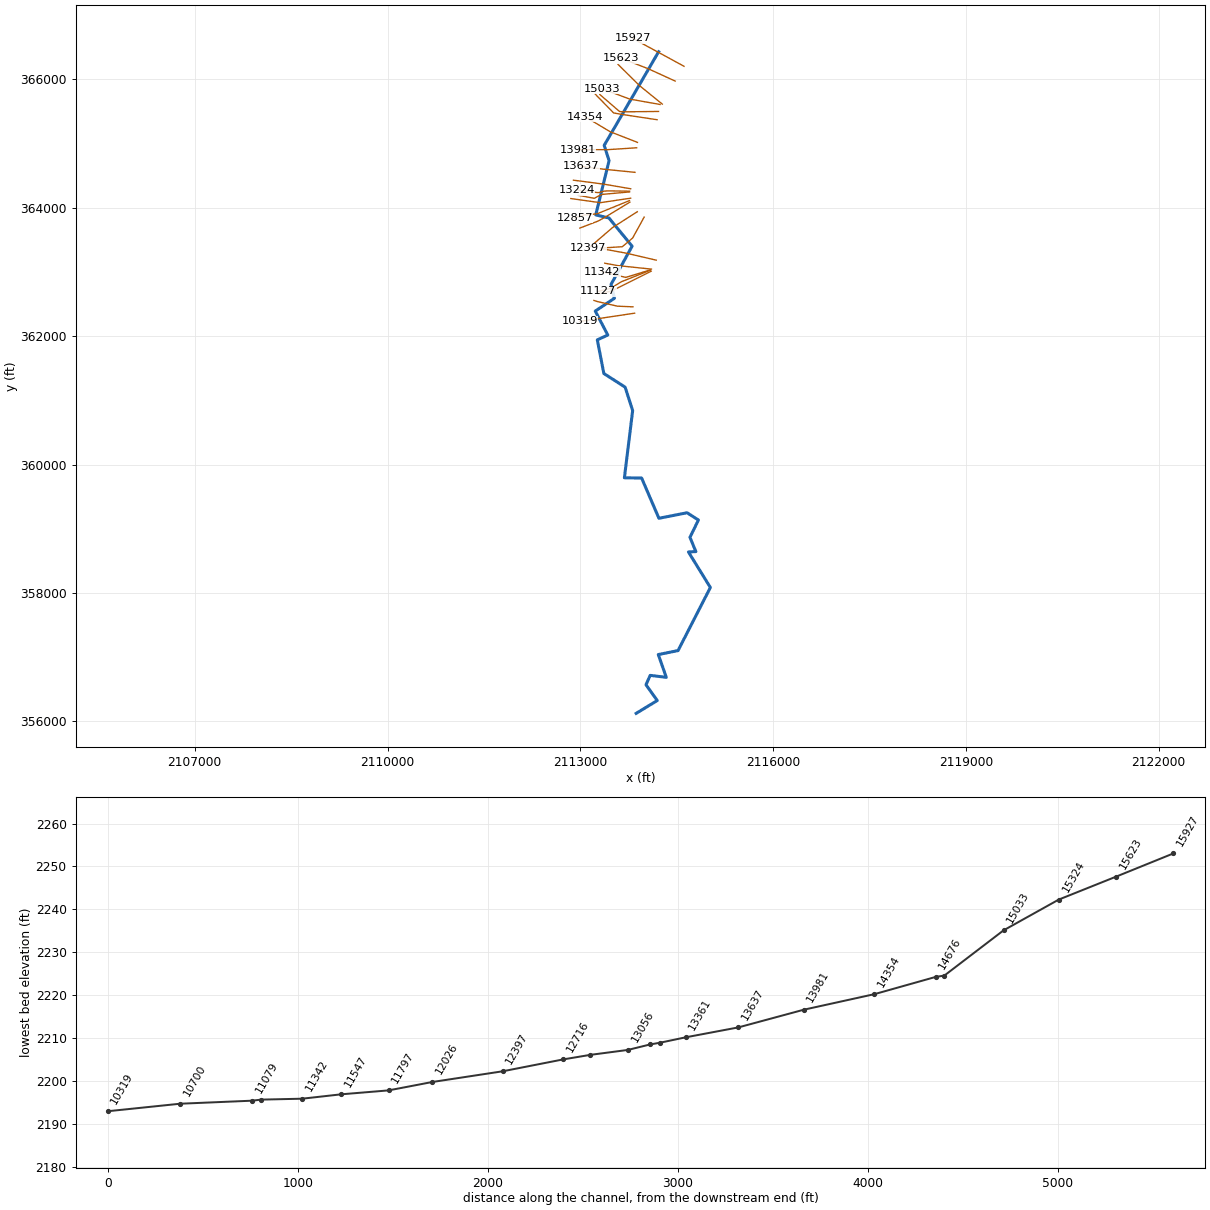
--- SNKNGCKT1.prj (project) ---

Proj Title=SNKNGCKT1
Current Plan=p01
Default Exp/Contr=0.3,0.1
English Units
Geom File=g01
Flow File=f01
Plan File=p01
Y Axis Title=Elevation
X Axis Title(PF)=Main Channel Distance
X Axis Title(XS)=Station
BEGIN DESCRIPTION:
Stream Name- Sinking Creek Tributary 1
Flood Zone: Zone A
Greenbrier County, WV
County-Wide Study
WVDHSEM-2018-3, Flood Risk Project
HEC-RAS Version: 5.0.7
General Notes:
For the Hydrology regression  was used.
END DESCRIPTION:
DSS Export Rating Curves= 0
DSS Export Rating Curve Sorted= 0
DSS Export Volume Flow Curves= 0
DXF Filename=SNKNGCKT1.F2.
DXF OffsetX= 0
DXF OffsetY= 0
DXF ScaleX= 1
DXF ScaleY= 10

--- SNKNGCKT1.p01 (plan) ---

Plan Title=Floodplain
Program Version=5.07
Short Identifier=Floodplain
Geom File=g01
Flow File=f01
Subcritical Flow
K Sum by GR= 0
Std Step Tol= 0.01
Critical Tol= 0.01
Num of Std Step Trials= 20
Max Error Tol= 0.3
Flow Tol Ratio= 0.001
Split Flow NTrial= 30
Split Flow Tol= 0.02
Split Flow Ratio= 0.02
Log Output Level= 0
Friction Slope Method= 1
Unsteady Friction Slope Method= 2
Unsteady Bridges Friction Slope Method= 1
Parabolic Critical Depth
Global Vel Dist= 0 , 0 , 0
Global Log Level= 0
CheckData=True
Encroach Param=-1 ,0,0, 0
Computation Interval=1MIN
Output Interval=1HOUR
Instantaneous Interval=1HOUR
Mapping Interval=1HOUR
Computation Time Step Use Courant=        0
Computation Time Step Use Time Series=    0
Computation Time Step Count To Double=0
Computation Time Step Max Doubling=0
Computation Time Step Max Halving=0
Computation Time Step Residence Courant=0
Run HTab= 0
Run UNet= 0
Run Sediment= 0
Run PostProcess= 0
Run WQNet= 0
Run RASMapper= 0
UNET Theta= 1
UNET Theta Warmup= 1
UNET ZTol= 0.02
UNET ZSATol= 0.02
UNET MxIter= 20
UNET Max Iter WO Improvement= 0
UNET MaxInSteps= 0
UNET DtIC= 0
UNET DtMin= 0
UNET MaxCRTS= 20
UNET WFStab= 2
UNET SFStab= 1
UNET WFX= 1
UNET SFX= 1
UNET 1D Methodology=Finite Difference
UNET DSS MLevel= 4
UNET Pardiso=0
UNET DZMax Abort= 100
UNET Use Existing IB Tables=-1
UNET Froude Reduction=False
UNET Froude Limit= 0.8
UNET Froude Power= 4
UNET D1 Cores= 0
UNET D2 Coriolis=0
UNET D2 Cores= 0
UNET D2 Theta= 1
UNET D2 Theta Warmup= 1
UNET D2 Z Tol= 0.01
UNET D2 Volume Tol= 0.01
UNET D2 Max Iterations= 20
UNET D2 Equation= 0
UNET D2 RampUpFraction=0.1
UNET D2 TimeSlices= 1
UNET D2 BCVolumeCheck=0
UNET D1D2 MaxIter= 0
UNET D1D2 ZTol=0.01
UNET D1D2 QTol=0.1
UNET D1D2 MinQTol=1
Write IC File= 0
Write IC File at Fixed DateTime=0
Write IC File at Sim End=0
Echo Input=False
Echo Parameters=False
Echo Output=False
Write Detailed= 0
HDF Write Warmup=0
HDF Write Time Slices=0
HDF Flush=0
HDF Face Node Velocities=0
HDF Compression= 1
HDF Chunk Size= 1
HDF Spatial Parts= 1
HDF Use Max Rows=0
HDF Fixed Rows= 1
Calibration Method= 0
Calibration Iterations= 20
Calibration Max Change=0.05
Calibration Tolerance=0.2
Calibration Maximum=1.5
Calibration Minimum=0.5
Calibration Optimization Method= 1
WQ AD Non Conservative
WQ ULTIMATE=-1
WQ Max Comp Step=1HOUR
WQ Output Interval=15MIN
WQ Output Selected Increments= 0
WQ Output face flow=0
WQ Output face velocity=0
WQ Output face area=0
WQ Output face dispersion=0
WQ Output cell volume=0
WQ Output cell surface area=0
WQ Output cell continuity=0
WQ Output cumulative cell continuity=0
WQ Output face conc=0
WQ Output face dconc_dx=0
WQ Output face courant=0
WQ Output face peclet=0
WQ Output face adv mass=0
WQ Output face disp mass=0
WQ Output cell mass=0
WQ Output cell source sink temp=0
WQ Output nsm pathways=0
WQ Output nsm derived pathways=0
WQ Output MaxMinRange=-1
WQ Daily Max Min Mean=-1
WQ Daily Range=0
WQ Daily Time=0
WQ Create Restart=0
WQ Fixed Restart=0
WQ System Summary=0
WQ Write To DSS=0
WQ Use Fixed Temperature=0
Sorting and Armoring Iterations= 10
XS Update Threshold= 0.02
Bed Roughness Predictor= 0
Hydraulics Update Threshold= 0.02
Energy Slope Method= 1
Volume Change Method= 1
Sediment Retention Method= 0
XS Weighting Method= 0
Number of US Weighted Cross Sections= 1
Number of DS Weighted Cross Sections= 1
Upstream XS Weight=0
Main XS Weight=1
Downstream XS Weight=0
Number of DS XS's Weighted with US Boundary= 1
Upstream Boundary Weight= 1
Weight of XSs Associated with US Boundary= 0
Number of US XS's Weighted with DS Boundary= 1
Downstream Boundary Weight= 0.5
Weight of XSs Associated with DS Boundary= 0.5
Percentile Method= 0
Sediment Output Level= 3
Mass or Volume Output= 0
Output Increment Type= 1
Profile and TS Output Increment= 1
XS Output Flag= 0
XS Output Increment= 10
Write Gradation File= 0
Read Gradation Hotstart= 0
Write HDF5 File= 1
Write Binary Output= 1
Write DSS Sediment File= 0
SV Curve= 0
Specific Gage Flag= 0

--- SNKNGCKT1.f01 (steady flow) ---

Flow Title=Flow
Program Version=5.07
Number of Profiles= 6
Profile Names=f1p,f10p,f4p,f2p,f02p,f1pplus
River Rch & RM=FLYNNCK,Main            ,9788
     547     289     384     463     765     810
River Rch & RM=FLYNNCK,Main            ,8346
     617     327     434     523     861     912
River Rch & RM=FLYNNCK,Main            ,2542
     689     367     486     584     959    1020
River Rch & RM=HUGHRTCK,Main            ,26252
     536     283     376     454     750     793
River Rch & RM=HUGHRTCK,Main            ,25696
     596     316     419     505     832     882
River Rch & RM=HUGHRTCK,Main            ,21314
     890     479     631     757    1230    1320
River Rch & RM=HUGHRTCK,Main            ,18981
     994     536     706     845    1370    1470
River Rch & RM=HUGHRTCK,Main            ,16952
    1100     599     786     940    1520    1630
River Rch & RM=HUGHRTCK,Main            ,13127
    1280     695     911    1090    1760    1890
River Rch & RM=HUGHRTCK,Main            ,7853
    2240    1250    1620    1920    3050    3320
River Rch & RM=HUGHRTCKT1,Main            ,3576
     413     215     288     348     580     610
River Rch & RM=SNKNGCKT1,Main            ,15927
     161    81.1     110     135     230     238
River Rch & RM=SNKNGCKT1,Main            ,15623
     182      92     125     153     260     269
River Rch & RM=SNKNGCKT1,Main            ,13637
     351     182     244     296     495     519
River Rch & RM=SNKNGCKT1,Main            ,12716
     412     215     287     348     579     609
River Rch & RM=SNKNGCKT1,Main            ,10019
     582     308     409     493     812     860
River Rch & RM=SNKNGCKT1,Main            ,8301
     724     386     511     614    1010    1070
River Rch & RM=SNKNGCKT1,Main            ,7842
     808     433     572     686    1120    1190
River Rch & RM=SNKNGCKT2,Main            ,1987
     171    86.1     117     143     244     253
River Rch & RM=SNKNGCKT2,Main            ,1326
     191    96.8     131     160     273     283
River Rch & RM=SNKNGCKT3,Main            ,1878
     154    77.6     106     129     221     228
River Rch & RM=SNKNGCKT3,Main            ,756
     172    86.8     118     144     246     255
River Rch & RM=SNKNGCKT4,Main            ,1795
    27.9    13.1    18.5      23    41.2    41.3
River Rch & RM=SNKNGCKT4,Main            ,1597
      33    15.6    21.9    27.3    48.7    48.8
River Rch & RM=SNKNGCKT4,Main            ,987
    39.5    18.8    26.3    32.7      58    58.4
River Rch & RM=STONYRN,Main            ,5205
     582     308     409     493     813     861
River Rch & RM=STONYRN,Main            ,3401
     666     354     469     565     928     985
Boundary for River Rch & Prof#=FLYNNCK,Main            , 1
Up Type= 0
Dn Type= 3
Dn Slope=0.009659
Boundary for River Rch & Prof#=FLYNNCK,Main            , 2
Up Type= 0
Dn Type= 3
Dn Slope=0.009659
Boundary for River Rch & Prof#=FLYNNCK,Main            , 3
Up Type= 0
Dn Type= 3
Dn Slope=0.009659
Boundary for River Rch & Prof#=FLYNNCK,Main            , 4
Up Type= 0
Dn Type= 3
Dn Slope=0.009659
Boundary for River Rch & Prof#=FLYNNCK,Main            , 5
Up Type= 0
Dn Type= 3
Dn Slope=0.009659
Boundary for River Rch & Prof#=FLYNNCK,Main            , 6
Up Type= 0
Dn Type= 3
Dn Slope=0.009659
Boundary for River Rch & Prof#=HUGHRTCK,Main            , 1
Up Type= 0
Dn Type= 3
Dn Slope=0.002151
Boundary for River Rch & Prof#=HUGHRTCK,Main            , 2
Up Type= 0
Dn Type= 3
Dn Slope=0.002151
Boundary for River Rch & Prof#=HUGHRTCK,Main            , 3
Up Type= 0
Dn Type= 3
Dn Slope=0.002151
Boundary for River Rch & Prof#=HUGHRTCK,Main            , 4
Up Type= 0
Dn Type= 3
Dn Slope=0.002151
Boundary for River Rch & Prof#=HUGHRTCK,Main            , 5
Up Type= 0
Dn Type= 3
Dn Slope=0.002151
Boundary for River Rch & Prof#=HUGHRTCK,Main            , 6
Up Type= 0
Dn Type= 3
Dn Slope=0.002151
Boundary for River Rch & Prof#=HUGHRTCKT1,Main            , 1
Up Type= 0
Dn Type= 3
Dn Slope=0.008324
Boundary for River Rch & Prof#=HUGHRTCKT1,Main            , 2
Up Type= 0
Dn Type= 3
Dn Slope=0.008324
Boundary for River Rch & Prof#=HUGHRTCKT1,Main            , 3
Up Type= 0
Dn Type= 3
Dn Slope=0.008324
Boundary for River Rch & Prof#=HUGHRTCKT1,Main            , 4
Up Type= 0
Dn Type= 3
Dn Slope=0.008324
Boundary for River Rch & Prof#=HUGHRTCKT1,Main            , 5
Up Type= 0
Dn Type= 3
Dn Slope=0.008324
Boundary for River Rch & Prof#=HUGHRTCKT1,Main            , 6
Up Type= 0
Dn Type= 3
Dn Slope=0.008324
Boundary for River Rch & Prof#=SNKNGCKT1,Main            , 1
Up Type= 0
Dn Type= 3
Dn Slope=0.003593
Boundary for River Rch & Prof#=SNKNGCKT1,Main            , 2
Up Type= 0
Dn Type= 3
Dn Slope=0.003593
Boundary for River Rch & Prof#=SNKNGCKT1,Main            , 3
Up Type= 0
Dn Type= 3
Dn Slope=0.003593
Boundary for River Rch & Prof#=SNKNGCKT1,Main            , 4
Up Type= 0
Dn Type= 3
Dn Slope=0.003593
Boundary for River Rch & Prof#=SNKNGCKT1,Main            , 5
Up Type= 0
Dn Type= 3
Dn Slope=0.003593
Boundary for River Rch & Prof#=SNKNGCKT1,Main            , 6
Up Type= 0
Dn Type= 3
Dn Slope=0.003593
Boundary for River Rch & Prof#=SNKNGCKT2,Main            , 1
Up Type= 0
Dn Type= 3
Dn Slope=0.006517
Boundary for River Rch & Prof#=SNKNGCKT2,Main            , 2
Up Type= 0
Dn Type= 3
Dn Slope=0.006517
Boundary for River Rch & Prof#=SNKNGCKT2,Main            , 3
Up Type= 0
Dn Type= 3
Dn Slope=0.006517
Boundary for River Rch & Prof#=SNKNGCKT2,Main            , 4
Up Type= 0
Dn Type= 3
Dn Slope=0.006517
Boundary for River Rch & Prof#=SNKNGCKT2,Main            , 5
Up Type= 0
Dn Type= 3
Dn Slope=0.006517
Boundary for River Rch & Prof#=SNKNGCKT2,Main            , 6
Up Type= 0
Dn Type= 3
Dn Slope=0.006517
Boundary for River Rch & Prof#=SNKNGCKT3,Main            , 1
Up Type= 0
Dn Type= 3
Dn Slope=0.00548
Boundary for River Rch & Prof#=SNKNGCKT3,Main            , 2
Up Type= 0
Dn Type= 3
Dn Slope=0.00548
Boundary for River Rch & Prof#=SNKNGCKT3,Main            , 3
Up Type= 0
Dn Type= 3
Dn Slope=0.00548
Boundary for River Rch & Prof#=SNKNGCKT3,Main            , 4
Up Type= 0
Dn Type= 3
Dn Slope=0.00548
Boundary for River Rch & Prof#=SNKNGCKT3,Main            , 5
Up Type= 0
Dn Type= 3
Dn Slope=0.00548
Boundary for River Rch & Prof#=SNKNGCKT3,Main            , 6
Up Type= 0
Dn Type= 3
Dn Slope=0.00548
Boundary for River Rch & Prof#=SNKNGCKT4,Main            , 1
Up Type= 0
Dn Type= 3
Dn Slope=0.00461
Boundary for River Rch & Prof#=SNKNGCKT4,Main            , 2
Up Type= 0
Dn Type= 3
Dn Slope=0.00461
Boundary for River Rch & Prof#=SNKNGCKT4,Main            , 3
Up Type= 0
Dn Type= 3
Dn Slope=0.00461
Boundary for River Rch & Prof#=SNKNGCKT4,Main            , 4
Up Type= 0
Dn Type= 3
Dn Slope=0.00461
Boundary for River Rch & Prof#=SNKNGCKT4,Main            , 5
Up Type= 0
Dn Type= 3
Dn Slope=0.00461
Boundary for River Rch & Prof#=SNKNGCKT4,Main            , 6
Up Type= 0
Dn Type= 3
Dn Slope=0.00461
Boundary for River Rch & Prof#=STONYRN,Main            , 1
Up Type= 0
Dn Type= 3
Dn Slope=0.005293
Boundary for River Rch & Prof#=STONYRN,Main            , 2
Up Type= 0
Dn Type= 3
Dn Slope=0.005293
Boundary for River Rch & Prof#=STONYRN,Main            , 3
Up Type= 0
Dn Type= 3
Dn Slope=0.005293
Boundary for River Rch & Prof#=STONYRN,Main            , 4
Up Type= 0
Dn Type= 3
Dn Slope=0.005293
Boundary for River Rch & Prof#=STONYRN,Main            , 5
Up Type= 0
Dn Type= 3
Dn Slope=0.005293
Boundary for River Rch & Prof#=STONYRN,Main            , 6
Up Type= 0
Dn Type= 3
Dn Slope=0.005293
DSS Import GetInterval= 0
DSS Import GetPeak= 0
DSS Import FillOption= 0

--- SNKNGCKT1.g01 (geometry) ---

Geom Title=Geometry
Program Version=5.07

River Reach=SNKNGCKT1       ,Main
Reach XY= 30
2114219.31248297366428.6179271492113372.14062089 364970.75535731
2113448.25168914364732.9776176362113240.93550272363888.103979304
2113445.47380756363840.1998756382113806.79821613363401.381527558
2113478.65320314362804.7485344712113531.55237556362589.683019727
2113233.25146297362390.1998228882113428.16544323362017.369859889
2113264.99943097361942.3788681482113366.91720614 361418.00262031
2113697.72855239361205.9679393922113815.23258246360841.447014898
2113686.82568705359794.1489126382113954.47049297359790.398920149
2114223.94469155359163.9011573942114662.15739781359249.697901815
2114838.78368497359136.8460933862114706.78165239358867.240989566
2114798.92648122358645.4999632242114683.16063663358639.863163471
2115024.44702755358086.0890085552114521.63044789357103.648060054
2114214.17601031357041.7630132292114338.78960621356686.725993648
2114087.75111233356717.4218683172114022.71007867356571.009160226
2114198.07039946356325.5951542262113869.34861597356125.836039305

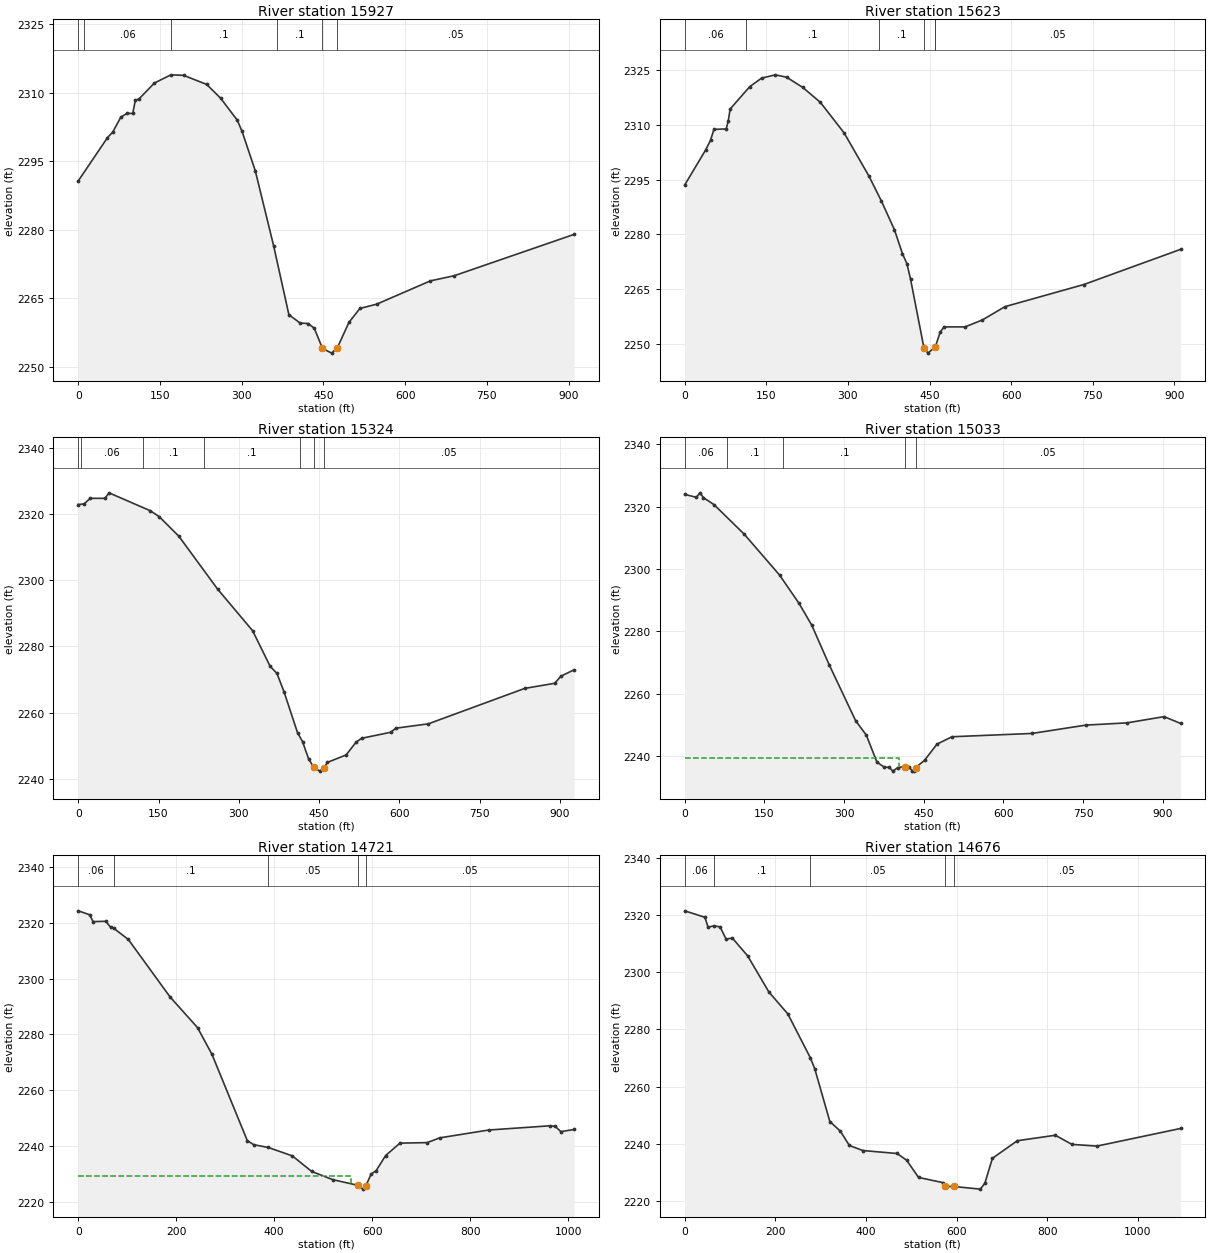
Type RM Length L Ch R = 1 ,15927   ,299,303.2,300.7
XS GIS Cut Line= 3
2114614.59187613 366202.082947152114215.08184838366419.837104812
2113815.57313298366637.591918647
#Sta/Elev= 30
       0 2290.68    53.7 2300.15    63.3 2301.36    78.2 2304.63    89.4 2305.45
     100 2305.44   104.8 2308.29   111.9 2308.65   139.8 2312.09   170.1 2313.88
   193.4 2313.77   235.8 2311.78   261.3 2308.77   291.9 2303.96   300.7  2301.5
   324.9 2292.91   358.5 2276.54   386.6 2261.44   407.2 2259.62     422 2259.52
   433.2 2258.48   448.2 2254.07   465.1 2253.05   475.7 2254.28   496.7 2259.75
   516.9 2262.82   547.4 2263.74   646.2 2268.84     690 2269.97     910 2279.01
#Mann= 6 ,-1 , 0
       0     .05       0   11.51     .06       0   170.1      .1       0
  364.65      .1       0   448.2    .045       0   475.7     .05       0
Bank Sta=448.2,475.7
XS Rating Curve= 0 ,0
Exp/Cntr=0.3,0.1

Type RM Length L Ch R = 1 ,15623   ,303.5,299.7,298.7
XS GIS Cut Line= 3
2114477.47994563365971.7710718072114062.49094622366162.138145149
2113638.62696455 366326.72114931
#Sta/Elev= 30
       0  2293.5      39 2303.19    47.5 2305.74    53.8 2308.69    76.3 2308.81
    79.9 2310.88    83.6 2314.26   119.6 2320.36   141.3 2322.67   166.6 2323.58
   187.4 2322.92   217.1 2320.13   249.3 2316.07   292.9 2307.74   338.4 2295.99
   361.5 2289.12   385.4 2281.31   400.2 2274.75   408.4 2272.01   415.1 2267.76
   439.8 2248.94   447.2 2247.61  460.71  2249.4   469.4 2253.31   476.5 2254.77
   515.2 2254.77   546.9 2256.66   588.6  2260.3   733.5 2266.34   911.3 2275.94
#Mann= 6 ,-1 , 0
       0     .06       0  112.83      .1       0  357.76      .1       0
   439.8    .045       0  460.71      .1       0  460.74     .05       0
Bank Sta=439.8,460.71
XS Rating Curve= 0 ,0
Exp/Cntr=0.3,0.1

Type RM Length L Ch R = 1 ,15324   ,285.1,291,294.9
XS GIS Cut Line= 3
 2114276.4101378365613.4929169712113922.16412714365900.820098221
2113587.84786664366231.650145233
#Sta/Elev= 30
       0 2322.81    10.9 2322.99    22.5 2324.68    50.1 2324.68    57.5 2326.34
   134.6 2320.94   151.5 2319.12   188.1 2313.22   260.4 2297.26   325.8 2284.71
   358.4    2274   371.2 2271.82   384.4 2266.31   409.7 2253.92   419.1  2251.2
   430.3 2246.05     440 2243.44   451.4  2242.3   458.7 2243.23   465.7 2244.95
   500.5 2247.19     519 2251.02   529.5 2252.22     584 2254.04   593.2 2255.26
   654.1 2256.58   834.1 2267.28   890.2 2268.83   901.8 2270.97   926.5 2272.91
#Mann= 7 ,-1 , 0
       0     .05       0    5.91     .06       0   120.4      .1       0
   234.9      .1       0  414.64     .05       0     440    .045       0
   458.7     .05       0
Bank Sta=440,458.7
XS Rating Curve= 0 ,0
Exp/Cntr=0.3,0.1

Type RM Length L Ch R = 1 ,15033   ,309.5,311.8,301.1
XS GIS Cut Line= 4
2114242.83896535365607.3583871072113843.66947977365678.589561909
2113780.25057607365687.4883428862113345.50386314365850.411078304
#Sta/Elev= 30
       0 2323.91    22.1 2322.97    28.8 2324.41    35.4 2322.86    55.4  2320.6
   112.1 2311.15   178.7 2298.02   215.4 2288.92   239.2 2281.96     272 2269.28
     322 2251.26     342 2246.68     362    2238   375.4 2236.44   385.4 2236.29
     392 2235.12   401.4 2236.28   415.3  2236.6   421.9 2236.52   428.5 2235.21
   431.9 2235.19   435.2 2236.27   451.7 2238.62   475.2  2243.8   503.3 2246.15
   653.9 2247.21   755.5 2249.89   832.6  2250.6   902.7  2252.6   933.8 2250.42
#Mann= 5 ,-1 , 0
       0     .06       0    79.7      .1       0   185.9      .1       0
   415.3    .045       0   435.2     .05       0
#XS Ineff= 2 , 0
          403.34 2239.47
Permanent Ineff=
       F       F
Bank Sta=415.3,435.2
XS Rating Curve= 0 ,0
Exp/Cntr=0.5,0.3

Type RM Length L Ch R = 1 ,14721   ,42.9,45,42.6
XS GIS Cut Line= 4
2114218.46766838365499.0505605642113673.63083155365493.030231386
2113611.92262164365497.5456423162113304.88780263 365762.43848522
#Sta/Elev= 30
       0 2324.29    23.6 2322.88    30.2 2320.42    56.4 2320.54    66.3 2318.36
    72.6 2318.03   102.3 2314.02   187.7 2293.39   243.5 2282.45     273 2272.88
   345.2 2241.93   358.3 2240.49   387.9  2239.5     437 2236.49   476.4 2230.93
   519.1 2227.99   571.4 2225.91   581.5 2224.57  586.852225.635   597.9 2229.97
   608.2  2231.2   627.5 2236.61   656.7 2241.05   712.5 2241.24     738 2242.94
   837.8 2245.75   963.5 2247.27   974.1 2247.02   985.1 2245.17  1012.3 2245.95
#Mann= 5 ,-1 , 0
       0     .06       0    72.6      .1       0   387.9     .05       0
   571.4    .045       0  586.85     .05       0
#XS Ineff= 2 , 0
             556 2229.16     601         2229.16
Permanent Ineff=
       F       F
Bank Sta=571.4,586.85
XS Rating Curve= 0 ,0
Exp/Cntr=0.5,0.3

Type RM Length L Ch R = 1 ,14676   ,316.5,322.4,313.5
XS GIS Cut Line= 5
2114196.57433946365370.1498997212113654.83329697365451.913515732
2113520.11309397365474.9692438992113260.98762797365739.808609232
2113234.14909898365768.458814397
#Sta/Elev= 30
       0 2321.42    44.7 2319.16    51.5 2315.73    64.8 2316.18    78.1 2315.82
    91.3 2311.56   105.2 2311.91     139 2305.69   185.9 2293.06   227.4 2285.48
   277.1 2270.19   287.1 2266.26   320.3 2247.87   343.5 2244.52   363.4  2239.5
   393.3 2237.74   468.5 2236.71   489.5 2234.41     516 2228.36   569.2 2226.56
  574.462225.233   593.5 2225.19   652.4 2224.27   662.4 2226.34     679 2235.04
   734.1 2241.17   817.8 2243.08   854.5 2239.89   909.6 2239.29  1094.3 2245.45
#Mann= 5 ,-1 , 0
       0     .06       0    64.8      .1       0   277.1     .05       0
  574.46    .045       0   593.5     .05       0
Bank Sta=574.46,593.5
XS Rating Curve= 0 ,0
Exp/Cntr=0.5,0.3

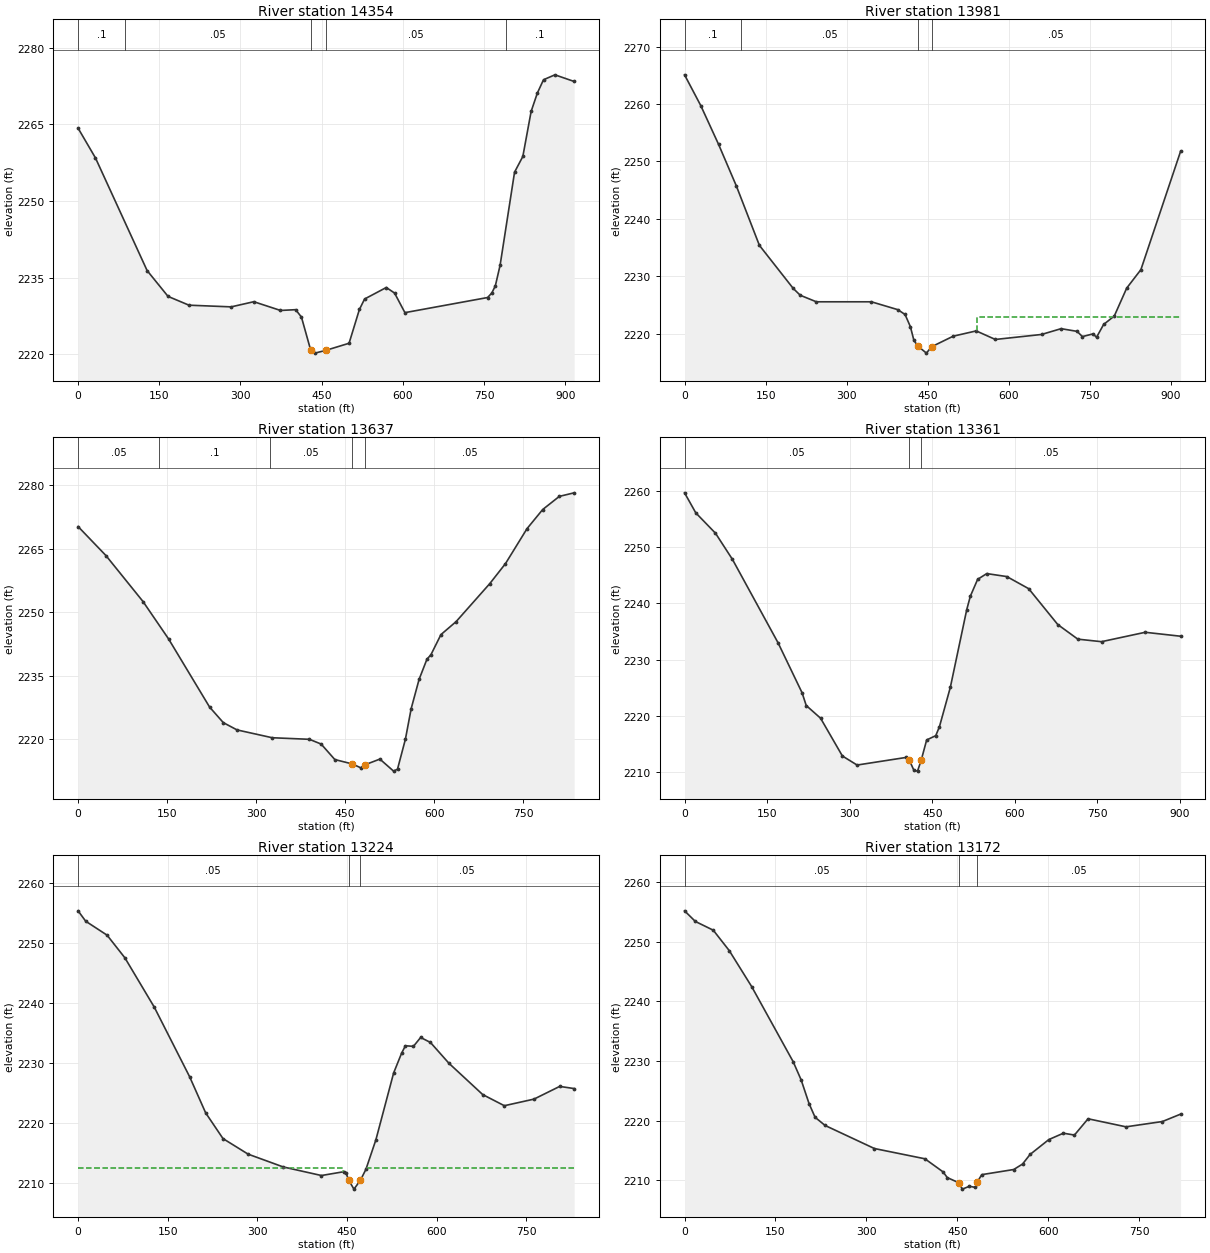
Type RM Length L Ch R = 1 ,14354   ,345.2,372.2,369.6
XS GIS Cut Line= 3
2113890.37711722365017.4658938052113464.65815239365183.489839971
2113070.23800947 365419.43490614
#Sta/Elev= 30
       0 2264.26    32.1 2258.44   127.5 2236.41   166.2 2231.35   204.9 2229.63
   282.9  2229.3   324.7 2230.31     374  2228.6     402 2228.75   412.7  2227.3
   429.8 2220.83   437.7 2220.25   458.6 2220.82   500.7 2222.18   519.8 2228.79
   529.4 2230.84   569.5 2233.09   584.8    2232   603.9 2228.17   756.7 2231.13
   764.5 2232.02     771 2233.42   779.8 2237.45   806.5 2255.66   821.8 2258.73
   837.1 2267.53   848.6 2271.13     860 2273.74   881.1  2274.7   916.6  2273.4
#Mann= 5 ,-1 , 0
       0      .1       0   86.92     .05       0   429.8    .045       0
   458.6     .05       0  791.04      .1       0
Bank Sta=429.8,458.6
XS Rating Curve= 0 ,0
Exp/Cntr=0.3,0.1

Type RM Length L Ch R = 1 ,13981   ,339.7,344,333.5
XS GIS Cut Line= 3
2113877.02806255364933.3381093142113420.75305647364903.664940313
2112959.85010688 364904.53403306
#Sta/Elev= 30
       0 2265.09      30 2259.73    62.9 2252.99    95.8 2245.75   138.5 2235.39
     201  2227.9   214.1  2226.7   243.9 2225.56   345.8 2225.56   394.7 2224.19
   408.1 2223.35     418 2221.22   424.5 2218.83   432.2 2217.82   447.6 2216.62
   457.2 2217.73   497.2 2219.57   539.8 2220.49   575.2    2219   660.7 2219.87
   696.9 2220.88   726.5 2220.41   736.3  2219.5     756 2219.97   762.5 2219.38
   775.6 2221.61   795.4 2223.09   818.3 2227.94   844.6 2231.16   918.1 2251.78
#Mann= 4 ,-1 , 0
       0      .1       0  104.21     .05       0   432.2    .045       0
   457.2     .05       0
#XS Ineff= 2 , 0
                          541.03         2222.89
Permanent Ineff=
       F       F
Bank Sta=432.2,457.2
XS Rating Curve= 0 ,0
Exp/Cntr=0.3,0.1

Type RM Length L Ch R = 1 ,13637   ,249,276.9,248.9
XS GIS Cut Line= 3
2113851.09241889364550.9543596512113373.19540881364598.694749728
2113020.25549789364643.077863067
#Sta/Elev= 30
       0 2270.22    46.9 2263.38   109.5 2252.51   152.4 2243.72   221.6 2227.62
   244.7 2223.95   267.8 2222.23   327.2 2220.38   389.8 2220.01   409.6 2218.89
   432.7 2215.23   462.3 2214.19   476.3 2213.29   483.2 2213.98   508.6 2215.34
   531.7  2212.5   538.3 2212.96   551.6 2220.02   561.4 2227.28   574.7 2234.16
   587.9 2238.91   594.6 2239.96   611.5 2244.72   637.1 2247.79   693.8 2256.75
   720.3 2261.48   756.6 2269.73     783 2274.24     811 2277.34     836 2278.18
#Mann= 5 ,-1 , 0
       0     .05       0  135.78      .1       0  323.57     .05       0
   462.3    .045       0   483.2     .05       0
Bank Sta=462.3,483.2
XS Rating Curve= 0 ,0
Exp/Cntr=0.3,0.1

Type RM Length L Ch R = 1 ,13361   ,139.3,136.5,145.1
XS GIS Cut Line= 3
2113785.19950606364295.0847926442113362.28007631364367.655841723
2112894.25312522364428.617990151
#Sta/Elev= 30
       0 2259.64    20.4 2256.08    56.2 2252.46      87 2247.81   169.9 2232.98
   213.5 2224.11     221 2221.85   247.1 2219.59   286.7 2212.88   313.4 2211.27
   402.9 2212.63   408.5 2212.09   416.6 2210.34   423.2 2210.19   429.9 2212.14
   439.8 2215.73   456.3 2216.49     463 2218.08   482.8 2225.08   512.6 2238.89
   519.2 2241.29   532.4 2244.27     549 2245.29   585.4 2244.76   625.1 2242.61
     678 2236.23   714.4 2233.64   757.4 2233.19   836.8 2234.86   901.1 2234.16
#Mann= 3 ,-1 , 0
       0     .05       0   408.5    .045       0   429.9     .05       0
Bank Sta=408.5,429.9
XS Rating Curve= 0 ,0
Exp/Cntr=0.5,0.3

Type RM Length L Ch R = 1 ,13224   ,46,51.7,54.9
XS GIS Cut Line= 6
2113767.89311022364257.3814559732113430.08768347364262.398506314
2113373.22920139364258.2177403872113326.40481997364244.002873808
2113277.90786973364234.8053856492112943.77074271364276.610092059
#Sta/Elev= 30
       0 2255.33    12.7  2253.6    48.5 2251.27    78.3 2247.49   127.5 2239.26
   186.6 2227.66   213.4 2221.64   242.4 2217.35   284.5 2214.75   343.2 2212.62
   407.1 2211.19   444.8 2211.83   448.1 2211.69   452.4 2210.47   461.5 2208.92
   472.1 2210.36   481.5 2212.21   498.2 2217.14   527.9 2228.29   541.2 2231.58
   547.6 2232.83     561 2232.73   573.1 2234.21   589.5 2233.38   620.5  2229.9
   676.9 2224.69   713.1 2222.83   762.7 2223.93   805.7 2226.05   829.9 2225.69
#Mann= 3 ,-1 , 0
       0     .05       0   452.4    .045       0   472.1     .05       0
#XS Ineff= 2 , 0
           442.4  2212.5   482.1          2212.5
Permanent Ineff=
       F       F
Bank Sta=452.4,472.1
XS Rating Curve= 0 ,0
Exp/Cntr=0.5,0.3

Type RM Length L Ch R = 1 ,13172   ,119,116,112.1
XS GIS Cut Line= 5
2113766.35669596364245.3716374782113344.93595089364207.745072305
 2113284.7329873364182.6604768042113218.67701705364146.705824316
2112967.80908047364192.922267318
#Sta/Elev= 30
       0  2255.2    17.8 2253.42    47.4 2251.95    73.8 2248.52   110.7  2242.5
   179.2  2229.9   192.4 2226.84   205.5 2222.85   215.4 2220.57   231.9  2219.2
   313.3 2215.33   396.6 2213.61   426.5 2211.42   433.6 2210.45   452.4  2209.6
   458.5 2208.52     470    2209   479.8 2208.81   483.3 2209.77   490.5 2210.95
   543.2 2211.81   557.8 2212.73   570.1 2214.33   601.1 2216.83   625.1  2217.9
   643.4 2217.59   665.9 2220.32   728.5 2218.97   788.6 2219.86   818.6  2221.1
#Mann= 3 ,-1 , 0
       0     .05       0   452.4    .045       0   483.3     .05       0
Bank Sta=452.4,483.3
XS Rating Curve= 0 ,0
Exp/Cntr=0.5,0.3

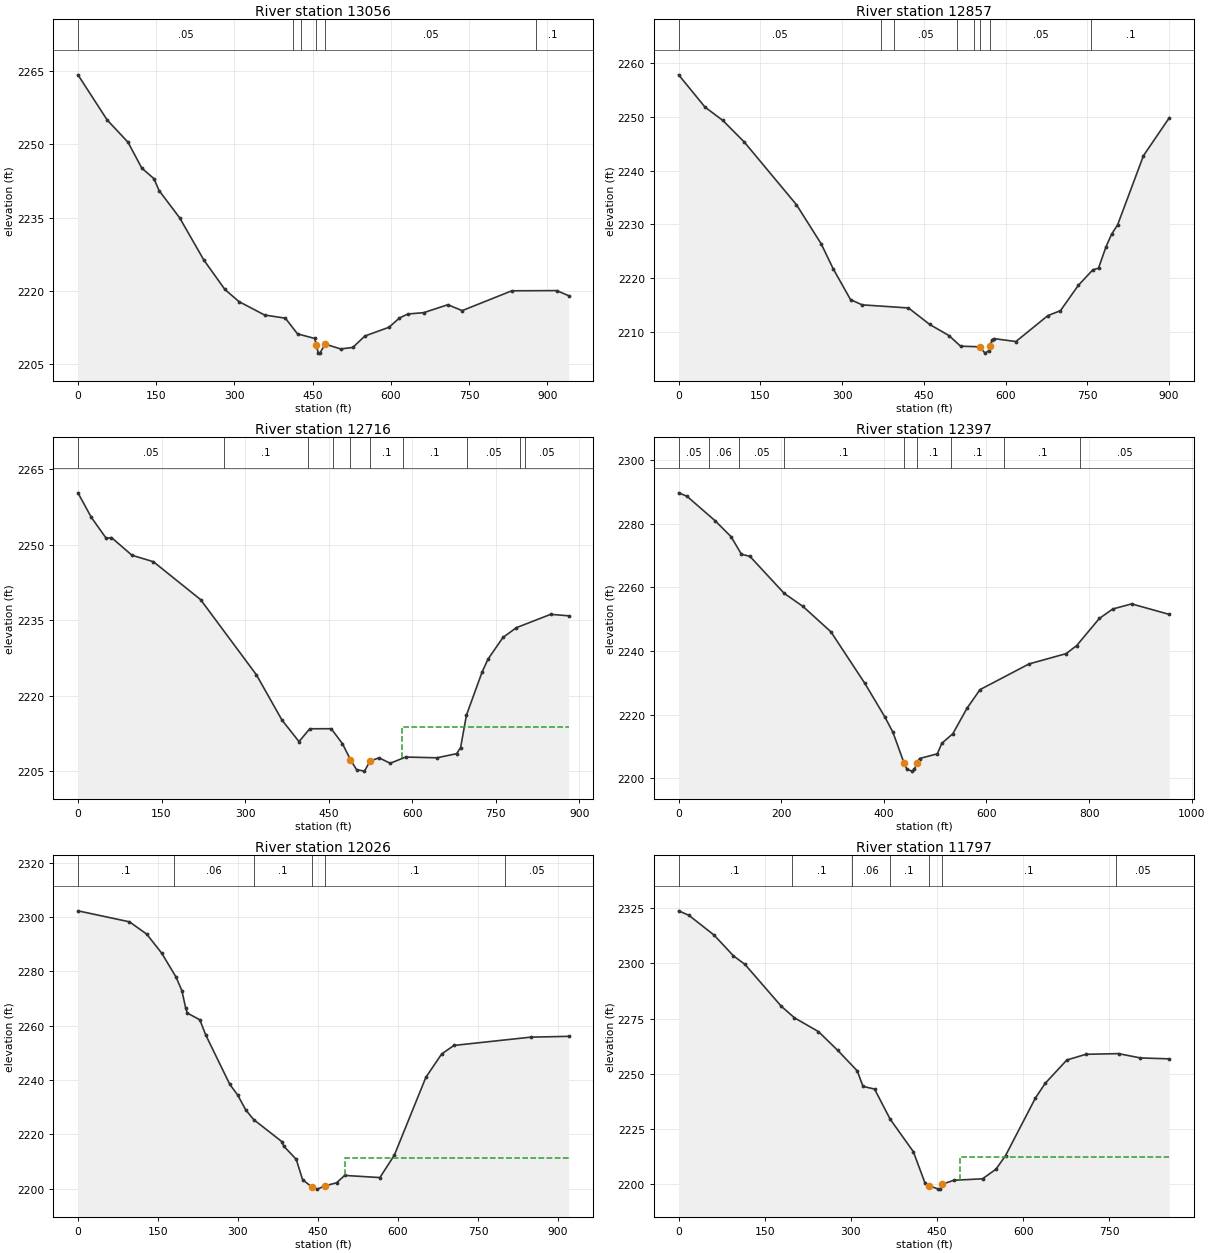
Type RM Length L Ch R = 1 ,13056   ,199.5,199.2,199.5
XS GIS Cut Line= 3
2113784.41407456364148.318025813 2113312.0498618364078.519937053
2112853.28896831364142.725845397
#Sta/Elev= 30
       0 2264.27      56 2255.02    95.8 2250.48   122.4 2245.16   145.6    2243
   155.5 2240.57   195.1 2234.95   241.3 2226.33   281.6 2220.31   308.5 2217.82
   357.8 2215.06   397.6 2214.41   420.9  2211.2     454 2210.25  456.552209.005
   460.7 2207.32   463.8 2207.25   473.9 2209.09   503.7 2208.11   526.9 2208.41
   550.1 2210.76   596.5 2212.56   616.4 2214.46   632.6 2215.27   662.8 2215.54
   709.1 2217.17   736.6 2215.96   831.7 2220.02     918 2220.06   940.7 2219.01
#Mann= 6 ,-1 , 0
       0     .05       0  412.92      .1       0  427.87     .05       0
  456.55    .045       0   473.9     .05       0  877.97      .1       0
Bank Sta=456.55,473.9
XS Rating Curve= 0 ,0
Exp/Cntr=0.3,0.1

Type RM Length L Ch R = 1 ,12857   ,133.4,141.5,135.1
XS GIS Cut Line= 5
2113765.03484821364110.7925103162113328.89726906363932.372591555
2113258.09557338363904.0517820572113052.77118088 363885.64368239
2112912.58412531363841.746460482
#Sta/Elev= 30
       0 2257.79    48.2 2251.81    80.9 2249.33   120.5  2245.3   216.2 2233.66
   261.5 2226.41   283.6 2221.76   315.5 2216.02   336.7 2215.06   421.8 2214.48
   460.8 2211.41   496.1 2209.35   517.4 2207.38   552.4 2207.27   562.2 2206.09
   568.8 2206.51  571.142207.437   575.4 2208.62   578.7 2208.79   618.9 2208.24
   677.5 2213.06   700.6 2213.97   733.5 2218.69   760.1 2221.57   770.5 2221.87
   784.2 2225.83   794.5 2228.18   805.4 2229.88     853 2242.77   900.5 2249.83
#Mann= 8 ,-1 , 0
       0     .05       0  371.02      .1       0   395.1     .05       0
  511.36      .1       0  541.51     .05       0   552.4    .045       0
  571.14     .05       0  757.51      .1       0
Bank Sta=552.4,571.14
XS Rating Curve= 0 ,0
Exp/Cntr=0.3,0.1

Type RM Length L Ch R = 1 ,12716   ,301.4,318.4,319.4
XS GIS Cut Line= 4
 2113772.3953978364087.2088960562113398.18354781  363858.8543659
2113280.95281114363793.5670948922112993.52982955363682.915413305
#Sta/Elev= 30
       0 2260.35      24 2255.48    50.7 2251.31    60.2 2251.46      97 2247.94
   135.4 2246.66   220.1 2239.13   320.4 2224.16     366 2215.21   396.7 2210.91
     416 2213.46   454.5 2213.47   474.7 2210.49  488.952207.332     500 2205.33
   514.2 2205.04   524.2 2207.04   540.4 2207.69   560.3  2206.6   588.2 2207.84
   644.4 2207.69   679.6 2208.51   686.7 2209.73   697.2 2216.17   725.3 2224.74
   735.8 2227.28   762.8 2231.62     787 2233.56   848.3  2236.2   880.6 2235.91
#Mann= 10 ,-1 , 0
       0     .05       0  262.35      .1       0  413.27      .1       0
  457.81      .1       0  488.95    .045       0   524.2      .1       0
  583.34      .1       0  698.35     .05       0  794.01      .1       0
  801.65     .05       0
#XS Ineff= 2 , 0
                          582.34         2213.89
Permanent Ineff=
       F       F
Bank Sta=488.95,524.2
XS Rating Curve= 0 ,0
Exp/Cntr=0.3,0.1

Type RM Length L Ch R = 1 ,12397   ,367.4,370.8,365.6
XS GIS Cut Line= 3
2113887.07791123 363937.451977732113502.81588447363691.297942474
 2113123.7431518363364.954106972
#Sta/Elev= 30
       0  2289.7    16.3 2288.61    70.9 2280.95   102.1 2275.94   122.4  2270.4
     139 2269.74   205.5 2258.15   242.3 2254.02   296.9 2246.02   363.1  2229.8
   402.1 2219.26   417.7 2214.46  439.072204.947   444.9 2202.84   454.9 2202.27
   459.6 2202.81   464.2 2204.86   469.6 2206.23   504.3 2207.71   512.9 2210.99
   534.6 2214.06   561.9 2221.99   587.5 2227.88   682.9 2235.94   755.4 2239.19
   775.9 2241.72     820 2250.23   846.3 2253.21     883 2254.81   956.5  2251.5
#Mann= 9 ,-1 , 0
       0     .05       0   59.17     .06       0  118.04     .05       0
  206.32      .1       0  439.07    .045       0   464.2      .1       0
  530.29      .1       0  634.85      .1       0  782.89     .05       0
Bank Sta=439.07,464.2
XS Rating Curve= 0 ,0
Exp/Cntr=0.3,0.1

Type RM Length L Ch R = 1 ,12026   ,236.3,229.5,211.5
XS GIS Cut Line= 4
 2113994.5032213363854.379309222 2113815.0232653363527.847153887
2113653.09675188363392.3792489772113317.41500856 363371.71852915
#Sta/Elev= 30
       0 2302.32    96.5 2298.27     129 2293.73   156.9 2286.75   183.6 2278.03
   194.8 2272.95   202.2 2266.34   205.2 2264.64   228.5 2262.17   239.7 2256.53
   284.6 2238.41   299.3 2234.49   314.6 2228.96   329.5 2225.39   382.1 2217.31
   385.9 2215.59   409.2 2210.77   421.2 2203.25  438.322200.593   448.8 2199.77
  463.942201.024   484.8 2202.09   500.1 2204.82   566.1 2204.03   593.3 2212.32
   652.3 2240.97   681.9 2249.57   704.9 2252.72   848.8 2255.77     920 2256.07
#Mann= 6 ,-1 , 0
       0      .1       0  179.45     .06       0  330.05      .1       0
  438.32    .045       0  463.94      .1       0  800.03     .05       0
#XS Ineff= 2 , 0
                          500.85         2211.31
Permanent Ineff=
       F       F
Bank Sta=438.32,463.94
XS Rating Curve= 0 ,0
Exp/Cntr=0.3,0.1

Type RM Length L Ch R = 1 ,11797   ,245.8,250,246.2
XS GIS Cut Line= 3
2114182.71445905363183.0666754842113718.97194822363291.373873562
2113346.55635448363359.613894567
#Sta/Elev= 30
       0 2323.81    17.9 2321.77    61.7 2312.84    95.3 2303.48   115.6 2299.53
   178.9 2280.58   201.8 2275.37   243.6 2269.12   277.3  2260.6   311.1 2251.37
   321.1 2244.35   341.3 2243.11   368.4 2229.52   408.7 2214.83   428.9 2200.78
  435.562199.452   452.5 2197.82   455.9 2197.91   459.2 2200.05   479.4 2201.83
   529.4  2202.5   552.8 2206.85   569.5 2213.03   621.5 2239.06   638.4 2245.68
   676.2 2256.27   709.5 2258.86   766.3 2259.16   804.4 2257.21   854.8  2256.8
#Mann= 7 ,-1 , 0
       0      .1       0  196.67      .1       0  302.61     .06       0
  367.84      .1       0  435.56    .045       0   459.2      .1       0
  762.29     .05       0
#XS Ineff= 2 , 0
                           490.1         2212.36
Permanent Ineff=
       F       F
Bank Sta=435.56,459.2
XS Rating Curve= 0 ,0
Exp/Cntr=0.3,0.1

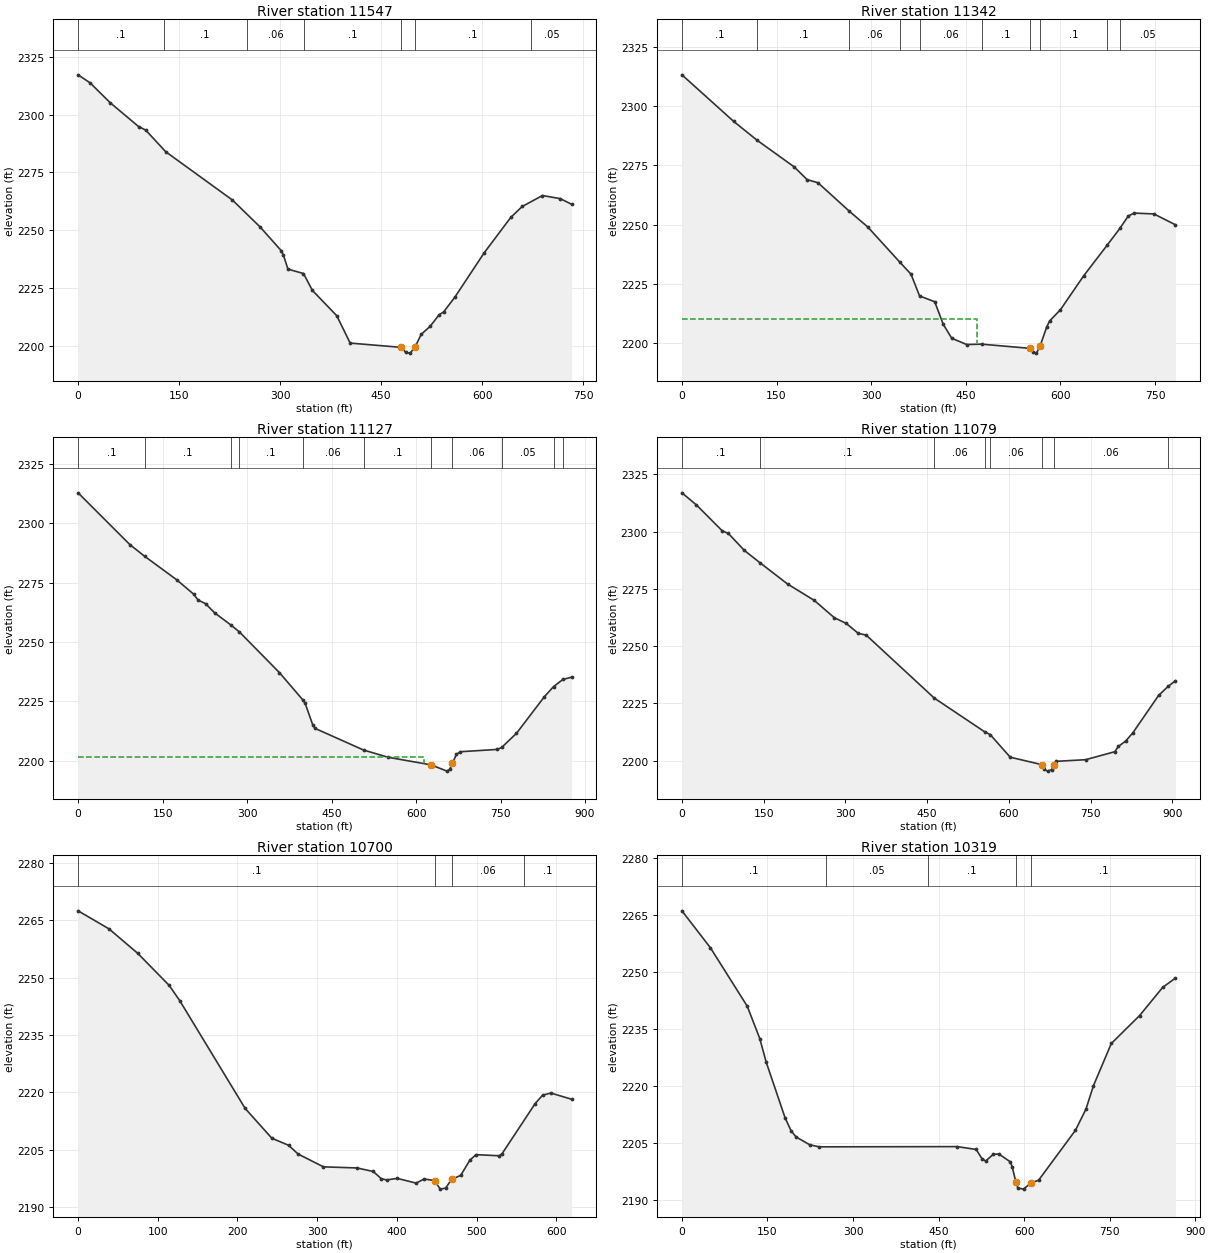
Type RM Length L Ch R = 1 ,11547   ,203.6,205.1,198.1
XS GIS Cut Line= 3
2114107.66670889363043.6972035622113587.66840506363098.227278233
 2113381.2308258363135.852202982
#Sta/Elev= 30
       0 2317.18    17.9 2313.69    47.6 2305.14    89.8 2294.83   100.4 2293.28
   129.9 2283.99     229 2263.09   270.2 2251.44   301.6 2241.17   304.9 2239.23
   311.5 2233.19   334.6 2231.31   347.8 2224.02   384.1 2213.03   403.9 2201.24
   479.92199.387   486.3 2197.24   492.9  2196.9   499.9 2199.36   509.4 2205.04
   522.6 2208.46     536 2213.49   542.6 2214.68   559.3 2221.08   602.9 2240.27
   642.4 2255.58   659.3 2260.28   689.4 2265.01   715.8 2263.67   732.7 2261.23
#Mann= 7 ,-1 , 0
       0      .1       0  126.86      .1       0  250.54     .06       0
  335.14      .1       0   479.9    .045       0   499.9      .1       0
  673.04     .05       0
Bank Sta=479.9,499.9
XS Rating Curve= 0 ,0
Exp/Cntr=0.3,0.1

Type RM Length L Ch R = 1 ,11342   ,186.3,214.9,218.2
XS GIS Cut Line= 3
2114089.50598405363031.0902733952113707.17735238362914.975676224
2113334.76110247363004.185799643
#Sta/Elev= 30
       0 2313.14    81.9 2293.55   119.6 2285.49   177.9 2274.37   198.5 2268.98
   215.7 2267.67   265.6 2255.62   294.5 2249.07   345.9 2234.08   363.1 2229.18
   376.8 2219.97   400.8 2217.53   414.3 2208.02   427.8 2202.14   451.4 2199.51
   475.2 2199.66   552.6 2197.87   556.5 2196.32     562 2195.88  567.582198.684
   578.3 2206.86     583 2209.45   600.1 2214.17   636.9 2228.44     674  2241.3
   694.3 2248.43   707.8 2253.69   717.1 2254.89   748.3 2254.53   782.5 2249.95
#Mann= 10 ,-1 , 0
       0      .1       0   119.6      .1       0   265.6     .06       0
   345.9      .1       0   376.8     .06       0   475.2      .1       0
   552.6    .045       0  567.58      .1       0     674      .1       0
   694.3     .05       0
#XS Ineff= 2 , 0
          468.14 2210.43
Permanent Ineff=
       F       F
Bank Sta=552.6,567.58
XS Rating Curve= 0 ,0
Exp/Cntr=0.5,0.3

Type RM Length L Ch R = 1 ,11127   ,55.7,47.6,44.2
XS GIS Cut Line= 4
2114086.67396872363025.4262427242113639.20800014362847.006323978
2113470.70013505362743.6361238962113279.53614731362696.906886637
#Sta/Elev= 30
       0 2312.86    91.9 2291.06   118.3 2286.12   175.2 2276.22     205 2270.22
   213.1  2267.7   226.2  2266.2   242.3 2262.34   271.2 2257.22   286.2 2254.33
   357.5 2237.14   399.2  2225.6   402.8  2224.4   416.9 2214.95   420.4  2213.7
   506.7 2204.56   550.6 2201.49   626.6 2198.31     655 2195.67   659.7  2196.4
   664.5 2198.94   671.7 2202.76   678.8 2203.84   744.5 2204.82     752 2205.65
   778.3 2211.59     828 2227.07     844 2231.24   860.6 2234.26   876.2 2235.23
#Mann= 11 ,-1 , 0
       0      .1       0   118.3      .1       0   271.2     .06       0
   286.2      .1       0   399.2     .06       0   506.7      .1       0
   626.6    .045       0   664.5     .06       0     752     .05       0
     844     .06       0   860.6      .1       0
#XS Ineff= 2 , 0
           613.6 2201.75   677.5         2201.75
Permanent Ineff=
       F       F
Bank Sta=626.6,664.5
XS Rating Curve= 0 ,0
Exp/Cntr=0.5,0.3

Type RM Length L Ch R = 1 ,11079   ,383.9,379.4,375
XS GIS Cut Line= 4
2114103.66606072363011.2658379822113520.26138763362719.563337401
2113465.03610438362696.9068866372113275.28779621362658.674023479
#Sta/Elev= 30
       0 2316.92    26.4 2311.67    74.1  2300.3    85.1 2299.21   114.5 2291.78
   143.8 2286.28   193.8 2277.12   242.9 2269.94   279.5 2262.42   301.5 2259.89
   323.6 2255.57   338.1  2254.8   462.9 2227.32   555.7 2212.54   565.5  2211.4
   602.3  2201.5   661.1  2198.2   664.3 2196.17   670.7 2195.42   678.5 2196.08
     682 2198.08   686.3 2199.69   740.6 2200.41   794.1 2203.89   800.8 2206.22
   814.2 2208.55   827.6 2212.25   874.5 2228.46   892.4 2232.51   905.5 2234.88
#Mann= 8 ,-1 , 0
       0      .1       0   143.8      .1       0   462.9     .06       0
   555.7      .1       0   565.5     .06       0   661.1    .045       0
     682     .06       0   892.4      .1       0
Bank Sta=661.1,682
XS Rating Curve= 0 ,0
Exp/Cntr=0.5,0.3

Type RM Length L Ch R = 1 ,10700   ,368.9,380.7,376.3
XS GIS Cut Line= 4
2113820.23191631362456.6409629732113577.19434464362466.788252398
2113262.54372722362539.7274109722113212.00609864362556.112220734
#Sta/Elev= 30
       0 2267.53    38.8 2262.81    74.9  2256.4   114.3 2248.02   127.5 2244.05
   209.6 2215.84   243.2 2208.02   264.2 2206.18   276.1 2203.89   307.9 2200.54
   350.1 2200.25   370.4 2199.33   380.5 2197.43   387.2 2197.12   400.7 2197.52
   424.2 2196.28   434.3 2197.36   447.4 2196.95   454.5 2194.71   461.3 2194.99
   468.72197.275   480.2 2198.31   491.6 2202.26   499.3 2203.73   528.6 2203.44
     532 2203.95   573.5 2217.06   582.9 2219.29   593.3 2219.85   619.4 2218.23
#Mann= 4 ,-1 , 0
       0      .1       0   447.4    .045       0   468.7     .06       0
  559.52      .1       0
Bank Sta=447.4,468.7
XS Rating Curve= 0 ,0
Exp/Cntr=0.3,0.1

Type RM Length L Ch R = 1 ,10319   ,301.5,300.4,302
XS GIS Cut Line= 3
2113845.57307297362357.5578278152113312.46816805362277.471373811
2112989.72668755362228.410120234
#Sta/Elev= 30
       0 2266.21      50 2256.48   114.6 2241.09   136.5 2232.59   147.8 2226.37
     181 2211.68   191.3 2208.36     200 2206.71   224.1 2204.63   240.7 2204.09
   482.9 2204.15     516  2203.4   526.1 2200.98   532.6 2200.35   545.9 2202.11
   555.8 2202.21   575.8 2200.15   579.1 2198.88   585.7 2194.77     589 2193.25
     599 2192.96   612.3 2194.61   625.5 2195.31   690.1 2208.45   708.5 2214.02
   721.7 2220.21     753  2231.3   802.5 2238.63     843 2246.05   865.5 2248.52
#Mann= 5 ,-1 , 0
       0      .1       0   253.1     .05       0  431.78      .1       0
   585.7    .045       0   612.3      .1       0
Bank Sta=585.7,612.3
XS Rating Curve= 0 ,0
Exp/Cntr=0.3,0.1