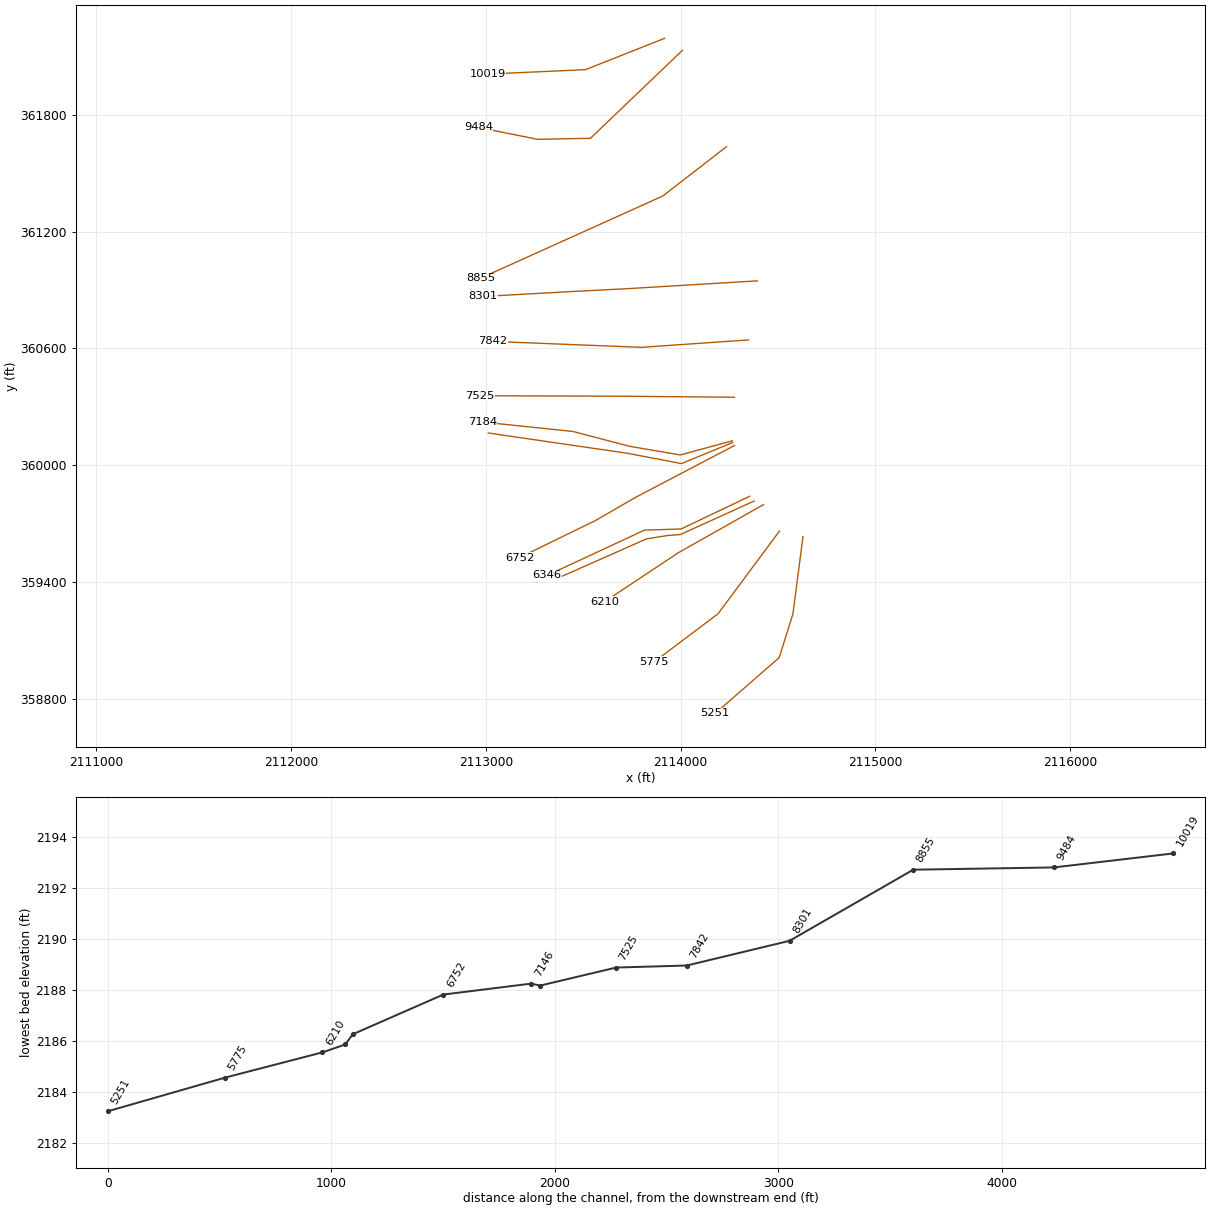
HEC-RAS study SNKNGCKT1.prj: SNKNGCKT1

--- SNKNGCKT1.g01 (geometry) --- (continued)

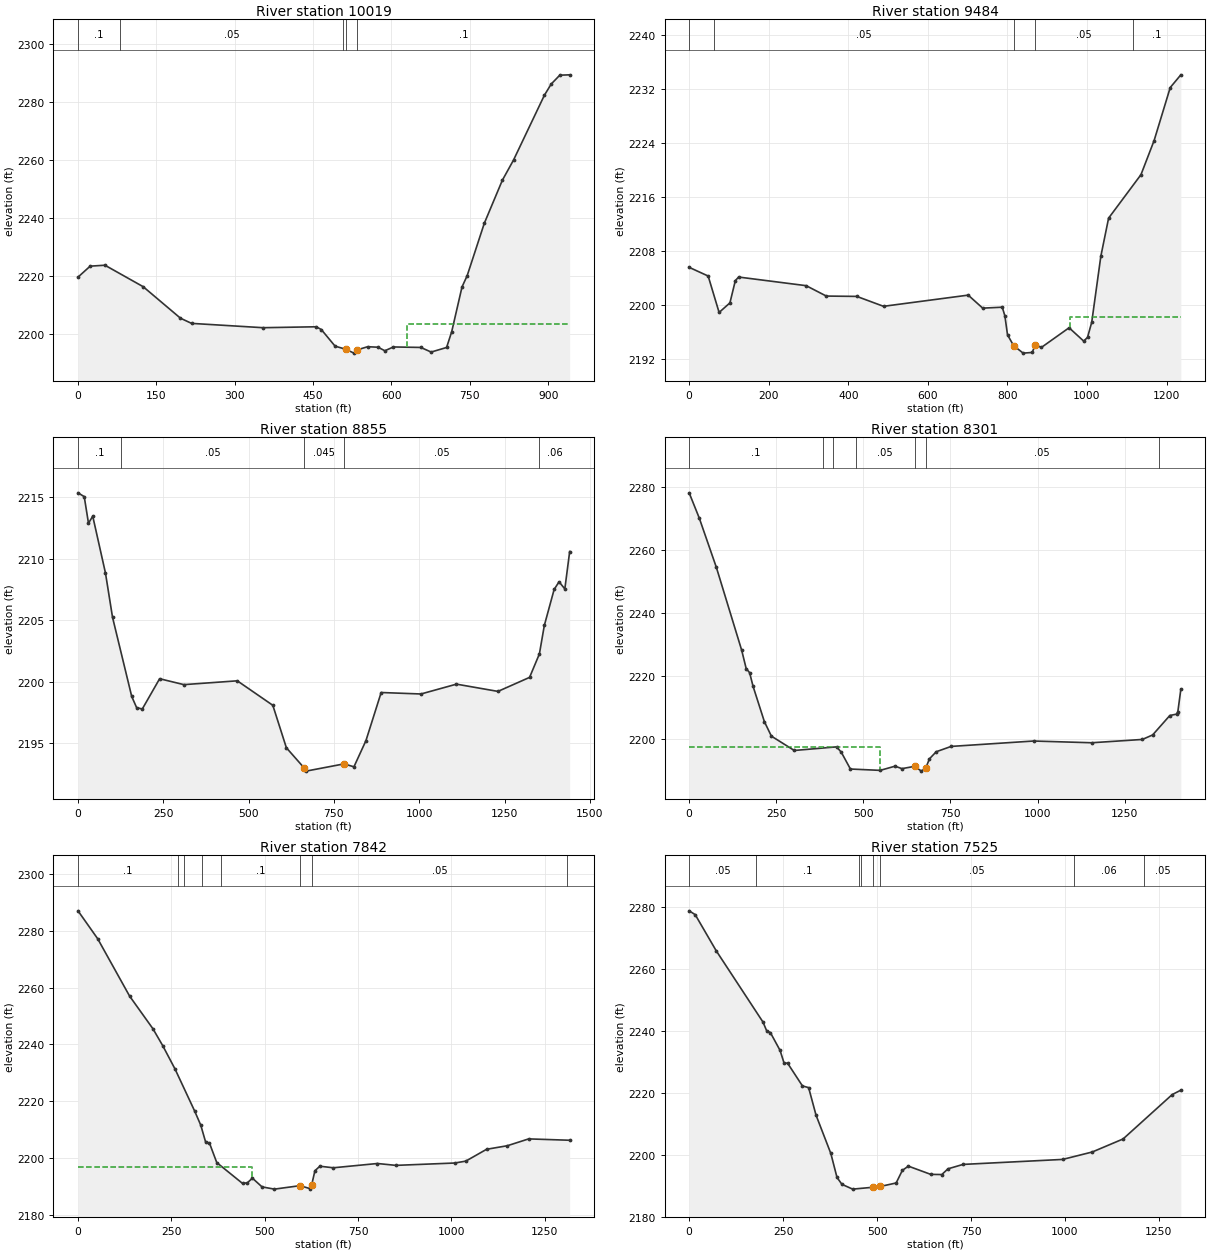
Type RM Length L Ch R = 1 ,10019   ,529.3,535,517.4
XS GIS Cut Line= 3
2113917.97515914362193.4246258882113511.40182531362032.359987393
2113008.02651972362009.706161305
#Sta/Elev= 30
       0 2219.57    23.3 2223.36    51.6 2223.68   124.8 2216.27   196.2  2205.4
   217.4 2203.62   354.2 2202.13     456 2202.45   465.8 2201.49   492.1 2195.77
   512.82194.683   528.2 2193.36   534.8 2194.51   554.5 2195.57   574.2  2195.4
   587.4 2194.18   603.8 2195.49   656.3 2195.32     676 2193.73   705.6 2195.31
   715.4 2200.78   735.1 2216.18     745 2220.09   777.8 2238.16   812.4 2253.02
   833.7 2259.95   892.8 2282.31   905.9 2286.19   922.3 2289.23   941.2 2289.35
#Mann= 5 ,-1 , 0
       0      .1       0   79.98     .05       0  507.61      .1       0
   512.8    .045       0   534.8      .1       0
#XS Ineff= 2 , 0
                          630.45         2203.52
Permanent Ineff=
       F       F
Bank Sta=512.8,534.8
XS Rating Curve= 0 ,0
Exp/Cntr=0.3,0.1

Type RM Length L Ch R = 1 ,9484    ,578.9,629.3,623.8
XS GIS Cut Line= 4
2114009.72005439362131.9234365672113537.25282347361679.675653398
 2113266.6070393361674.351517066 2112961.4245788361735.388468474
#Sta/Elev= 30
       0 2205.53    47.8 2204.24    75.3 2198.84   102.5 2200.26   116.1 2203.56
   124.4 2204.09   294.2 2202.81   344.8 2201.27   421.4 2201.22   488.6 2199.75
   701.5 2201.41   737.9 2199.48   787.1 2199.62   793.7 2198.33   800.3 2195.53
  815.542193.925   839.6 2192.81   862.6 2192.91   869.6 2194.04   885.6 2193.66
   955.1 2196.57   991.9 2194.59  1001.5 2195.15    1012 2197.39  1034.9 2207.17
  1054.4 2212.82  1135.8 2219.27  1168.8 2224.32  1209.4 2232.19    1236 2234.07
#Mann= 5 ,-1 , 0
       0      .1       0   63.12     .05       0  815.54    .045       0
   869.6     .05       0 1115.13      .1       0
#XS Ineff= 2 , 0
                           957.1          2198.1
Permanent Ineff=
       F       F
Bank Sta=815.54,869.6
XS Rating Curve= 0 ,0
Exp/Cntr=0.3,0.1

Type RM Length L Ch R = 1 ,8855    ,448.1,553.2,545.8
XS GIS Cut Line= 3
2114235.52537705  361636.14227592113908.48797339361382.916732475
2112972.30874339360960.314559311
#Sta/Elev= 30
       0 2215.34    18.3 2215.03    30.7 2212.87    43.2 2213.44    80.5 2208.82
   101.2 2205.22   157.4 2198.79   171.8 2197.88   188.4 2197.77   239.2 2200.23
   310.3 2199.75   466.8 2200.06   570.9 2198.07   610.6 2194.62     663 2192.97
   668.2 2192.72   779.8 2193.31   808.6 2193.07   843.8  2195.2   888.4 2199.11
    1005 2198.99  1109.1 2199.79  1230.6  2199.2  1323.3 2200.34  1352.1 2202.25
  1366.5 2204.56  1395.3 2207.49  1409.7 2208.11  1426.6 2207.53  1440.8 2210.57
#Mann= 5 ,-1 , 0
       0      .1       0  125.97     .05       0     663    .045       0
   779.8     .05       0  1352.1     .06       0
Bank Sta=663,779.8
XS Rating Curve= 0 ,0
Exp/Cntr=0.3,0.1

Type RM Length L Ch R = 1 ,8301    ,437.9,459.7,448.4
XS GIS Cut Line= 4
2114394.31442955360946.9904389832113726.93813963360906.766109973
2113433.60932997360891.6493423132112985.47866455360866.730100811
#Sta/Elev= 30
       0 2278.21    28.9 2270.24    78.2 2254.53   150.8 2228.26   163.7 2222.46
   173.5 2221.17   183.4 2216.84   215.9 2205.63     236 2201.03   301.7 2196.48
     423 2197.63   436.5 2195.95   462.8  2190.6   548.2 2190.17   590.9  2191.5
   610.7 2190.72   646.8 2191.44   666.6 2189.93  679.19 2190.95   689.6 2193.83
   709.1 2196.08     752 2197.77   988.5 2199.48  1155.2 2198.93  1300.7 2199.98
  1330.2 2201.41  1379.5 2207.57  1399.2 2208.02  1402.5 2208.77  1411.1 2215.87
#Mann= 7 ,-1 , 0
       0      .1       0  383.15     .05       0  412.54      .1       0
  477.69     .05       0   646.8    .045       0  679.19     .05       0
  1347.7     .06       0
#XS Ineff= 2 , 0
          546.92 2197.71
Permanent Ineff=
       F       F
Bank Sta=646.8,679.19
XS Rating Curve= 0 ,0
Exp/Cntr=0.3,0.1

Type RM Length L Ch R = 1 ,7842    ,311.3,316.3,313
XS GIS Cut Line= 3
2114349.09732839360643.3443927322113799.48031738360605.246043727
2113034.16984014 360635.76337114
#Sta/Elev= 30
       0 2287.13    52.7 2277.29   138.2 2257.05   200.7 2245.53     227 2239.55
   259.9 2231.32   312.5 2216.49   328.9 2211.49   342.1 2205.44   351.9 2205.28
   371.7 2198.32   440.7 2190.97   453.9 2191.22   467.1 2192.83     493 2189.74
   526.2 2188.96   594.5 2190.18   621.5 2189.14   626.1 2190.59   634.6 2195.45
   647.8 2197.04   683.9 2196.49   802.1    2198   851.3 2197.34    1009 2198.17
  1038.5 2198.83  1094.3 2203.01    1150 2204.27  1207.1 2206.68  1316.9  2206.2
#Mann= 8 ,-1 , 0
       0      .1       0  268.81      .1       0  284.42     .05       0
  331.11      .1       0  381.84      .1       0   594.5    .045       0
   626.1     .05       0 1310.21     .06       0
#XS Ineff= 2 , 0
          466.67 2196.73
Permanent Ineff=
       F       F
Bank Sta=594.5,626.1
XS Rating Curve= 0 ,0
Exp/Cntr=0.3,0.1

Type RM Length L Ch R = 1 ,7525    ,339.6,341,324.3
XS GIS Cut Line= 3
 2114276.5577753360348.755743057 2113697.1081468360354.026073724
2112968.31170414360356.384664804
#Sta/Elev= 30
       0 2278.83    16.1  2277.6    71.9 2265.94   196.6 2242.85   206.1  2240.1
   216.2 2239.46   241.9 2233.72   252.3 2229.73   262.2 2229.54   301.5 2222.23
   317.9 2221.69   337.6  2212.8     377  2200.4   393.4 2192.66   406.5 2190.43
   435.1 2188.88   488.1 2189.47   508.2 2189.73   550.8 2190.87   567.3 2194.94
   583.3 2196.31   642.8 2193.65   672.3 2193.59   688.7 2195.44   728.9 2196.87
   993.8 2198.48  1072.6 2200.88  1154.6 2205.09  1285.2 2219.43  1308.3 2220.87
#Mann= 8 ,-1 , 0
       0     .05       0  178.88      .1       0  452.61      .1       0
  456.41     .05       0   488.1    .045       0   508.2     .05       0
 1022.89     .06       0 1211.48     .05       0
Bank Sta=488.1,508.2
XS Rating Curve= 0 ,0
Exp/Cntr=0.3,0.1

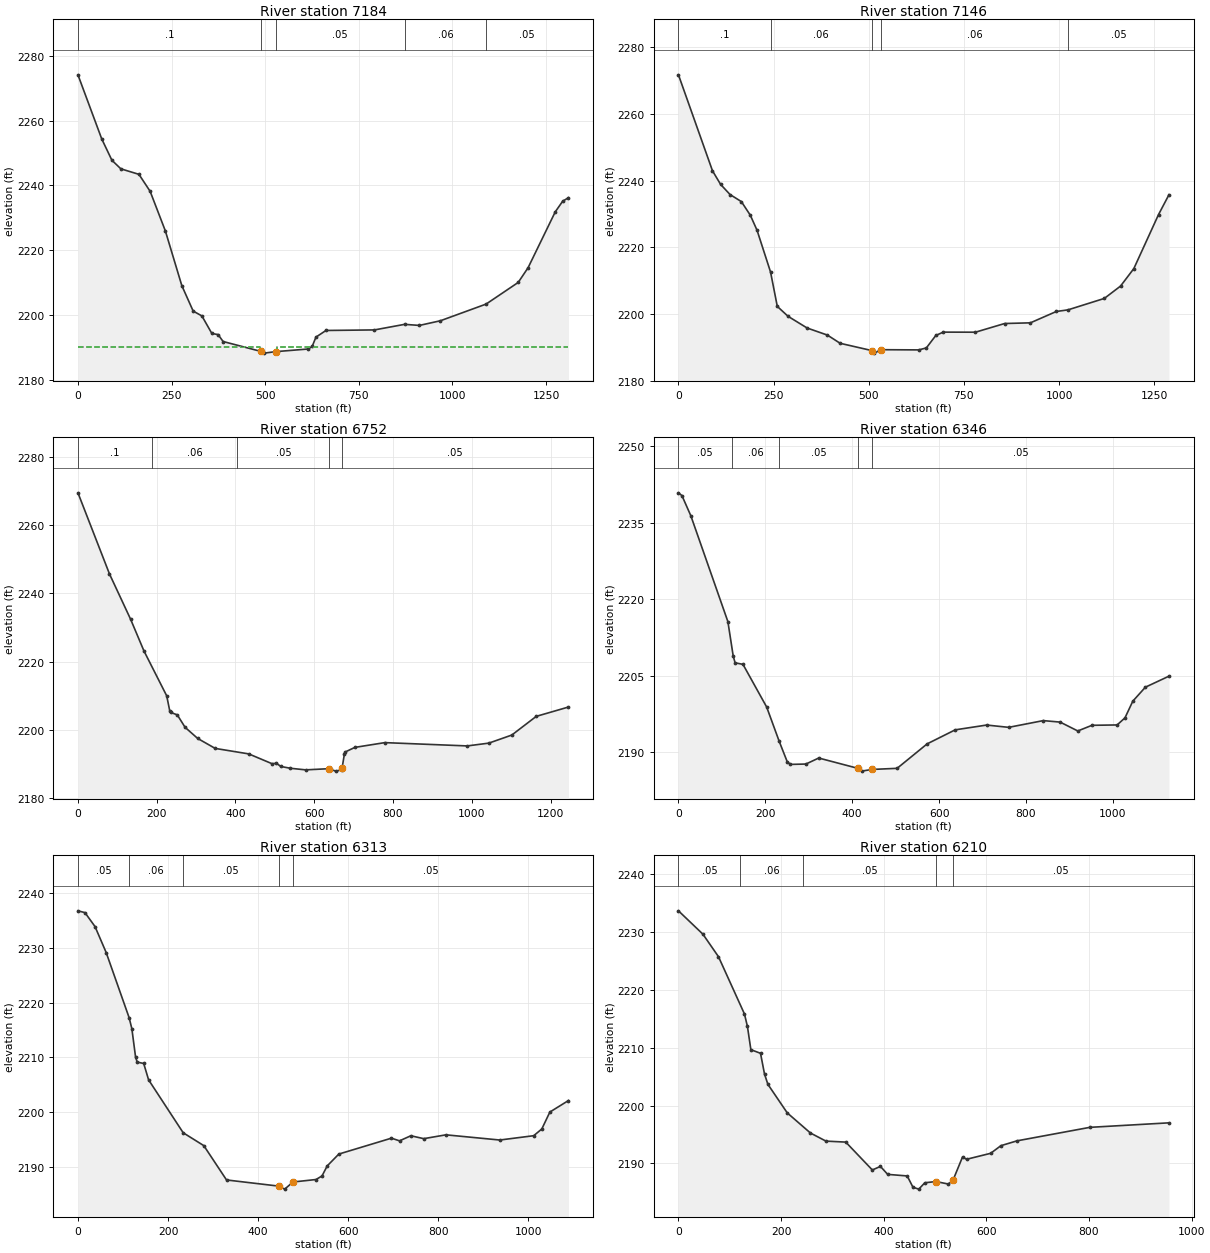
Type RM Length L Ch R = 1 ,7184    ,38.6,38.5,41.8
XS GIS Cut Line= 5
2114266.02465989360124.8001542242113998.31522155 360052.06965664
2113736.79540339360096.9458792212113447.42163831360172.771186888
2112981.95373721360221.441693231
#Sta/Elev= 30
       0 2274.14    63.6 2254.32    90.7 2247.75   114.6  2245.1   162.9  2243.4
   192.8 2238.15   233.5  2225.9   277.4 2209.02   307.7 2201.16     331 2199.66
   357.6 2194.24   374.3  2193.9   387.6 2191.76  488.392188.708   497.4 2188.17
   528.1 2188.63   615.3 2189.45   625.5 2190.25   635.6 2193.12   662.4 2195.17
   791.9 2195.34   872.2 2197.06   911.8 2196.73   967.9 2198.17  1089.9 2203.32
  1175.7 2210.01  1202.1 2214.56  1274.6 2231.81  1294.4 2235.09  1309.9 2236.19
#Mann= 5 ,-1 , 0
       0      .1       0  488.39    .045       0   528.1     .05       0
   872.2     .06       0  1089.9     .05       0
#XS Ineff= 2 , 0
          485.39    2190   531.1            2190
Permanent Ineff=
       F       F
Bank Sta=488.39,528.1
XS Rating Curve= 0 ,0
Exp/Cntr=0.3,0.1

Type RM Length L Ch R = 1 ,7146    ,366.6,393.9,394.9
XS GIS Cut Line= 4
2114267.67787181360116.0770745582114004.61048456360007.755440816
2113729.16385697360060.3688526452113012.83917414 360164.95656997
#Sta/Elev= 30
       0 2271.74    89.4 2242.95   110.7 2238.88   135.5 2235.83   165.3 2233.71
   188.8 2229.62   206.5 2225.11     242 2212.57   259.7 2202.27   287.9  2199.3
     338 2195.79   391.4 2193.66   424.8  2191.2  507.832189.022     515 2188.25
   531.7 2189.28   631.4 2189.22   651.3 2189.81   676.2 2193.55   695.6 2194.55
   780.3 2194.53   856.9 2197.13   924.7 2197.34   992.8 2200.74  1023.4 2201.23
  1118.9 2204.66  1161.5 2208.36  1196.5 2213.62  1261.4 2229.83  1288.8 2235.78
#Mann= 5 ,-1 , 0
       0      .1       0     242     .06       0  507.83    .045       0
   531.7     .06       0  1023.4     .05       0
Bank Sta=507.83,531.7
XS Rating Curve= 0 ,0
Exp/Cntr=0.3,0.1

Type RM Length L Ch R = 1 ,6752    ,410.3,405.5,391.2
XS GIS Cut Line= 4
2114277.09222305360100.723758817 2113770.1965833 359834.90703322
2113562.67009547359714.8551079782113173.16201623359524.825304314
#Sta/Elev= 30
       0 2269.53    80.1 2245.71   133.6 2232.44   167.6 2223.11   225.4 2209.92
   233.2 2205.46   235.7 2205.05   252.2 2204.34   272.1 2200.68     304 2197.42
   348.5 2194.49   433.7 2192.88     493 2189.99   504.1 2190.13     515 2189.19
   539.4 2188.66   578.2 2188.19   638.3 2188.54   654.1 2187.82   669.5 2188.18
  670.762188.749   676.4 2192.73   679.1 2193.47   703.1 2194.79   779.2 2196.19
   988.5 2195.22  1043.2 2196.04  1101.6 2198.41  1163.7  2203.9  1245.5 2206.64
#Mann= 5 ,-1 , 0
       0      .1       0  187.04     .06       0  404.69     .05       0
   638.3    .045       0  670.76     .05       0
Bank Sta=638.3,670.76
XS Rating Curve= 0 ,0
Exp/Cntr=0.3,0.1

Type RM Length L Ch R = 1 ,6346    ,32.1,33.4,38.5
XS GIS Cut Line= 5
2114355.11765756359839.8568264842114002.85700434359671.606708268
2113813.94476757359665.7117846352113739.49290456359630.481917143
2113315.53443488359433.606982812
#Sta/Elev= 30
       0 2240.86       8 2240.32    28.5 2236.36   113.8 2215.59   126.1 2208.82
   130.4 2207.51   148.5 2207.21   203.1 2198.83   231.9 2192.11   250.3 2188.12
   257.6 2187.58   293.4 2187.65   322.9 2188.83   412.5 2186.82   421.5 2186.26
  445.992186.591   503.4 2186.81   572.5 2191.61   637.1 2194.36   709.5  2195.3
   760.2 2194.85   839.8 2196.17   878.6 2195.88   919.3 2194.14   951.9 2195.25
  1009.8 2195.32  1027.9 2196.71  1045.9 2199.98  1074.9 2202.73  1129.2 2204.89
#Mann= 5 ,-1 , 0
       0     .05       0     123     .06       0   231.9     .05       0
   412.5    .045       0  445.99     .05       0
#XS Ineff= 2 ,-1
       0   402.5  2186.6  455.99  1128.9  2186.6
Permanent Ineff=
       F       F
Bank Sta=412.5,445.99
XS Rating Curve= 0 ,0
Exp/Cntr=0.3,0.1

Type RM Length L Ch R = 1 ,6313    ,95.7,102.4,112.4
XS GIS Cut Line= 5
2114376.99294189359814.8568764782113998.86771388359642.981892139
2113931.15951598359637.7735692262113825.95106497359621.106935889
2113369.70099323359419.023678645
#Sta/Elev= 30
       0 2236.81    15.6 2236.48    37.9 2233.93    62.7 2229.17   113.6 2217.25
   119.7 2215.22     128 2209.98   131.6 2209.12     146 2208.86   156.8 2205.87
   233.6 2196.18   279.4 2193.82   329.8 2187.54   445.8 2186.41     459 2185.86
   477.22187.162   528.5 2187.62   541.8 2188.28   553.3 2190.11   579.1 2192.28
   695.9 2195.19   713.8  2194.7   738.9 2195.63   767.6  2195.1   816.8  2195.8
   936.3 2194.85  1011.6 2195.64  1029.6 2196.87  1047.5 2199.97  1088.8 2202.08
#Mann= 5 ,-1 , 0
       0     .05       0   113.6     .06       0   233.6     .05       0
   445.8    .045       0   477.2     .05       0
Bank Sta=445.8,477.2
XS Rating Curve= 0 ,0
Exp/Cntr=0.3,0.1

Type RM Length L Ch R = 1 ,6210    ,428,435.1,419.8
XS GIS Cut Line= 3
2114425.34291081 359796.437950062113989.53800814359550.079846978
2113610.36094497359298.307056561
#Sta/Elev= 30
       0 2233.66    47.7 2229.62      78 2225.73   128.6 2215.83   134.4 2213.67
   141.1 2209.66   159.9 2209.03   167.7 2205.44   174.3 2203.66     212 2198.73
   257.2 2195.25   287.4 2193.85     326 2193.68   377.8 2188.86   393.5 2189.48
   407.7  2188.1   445.7 2187.83     457 2185.87   468.3 2185.55   480.1 2186.65
   501.8 2186.86   525.9 2186.43   534.9 2187.08   553.5  2191.1   561.4 2190.71
   608.3 2191.74   628.3 2193.06   659.8  2193.9   801.6 2196.23   955.8 2197.01
#Mann= 5 ,-1 , 0
       0     .05       0  120.85     .06       0  242.16     .05       0
   501.8    .045       0   534.9     .05       0
Bank Sta=501.8,534.9
XS Rating Curve= 0 ,0
Exp/Cntr=0.3,0.1

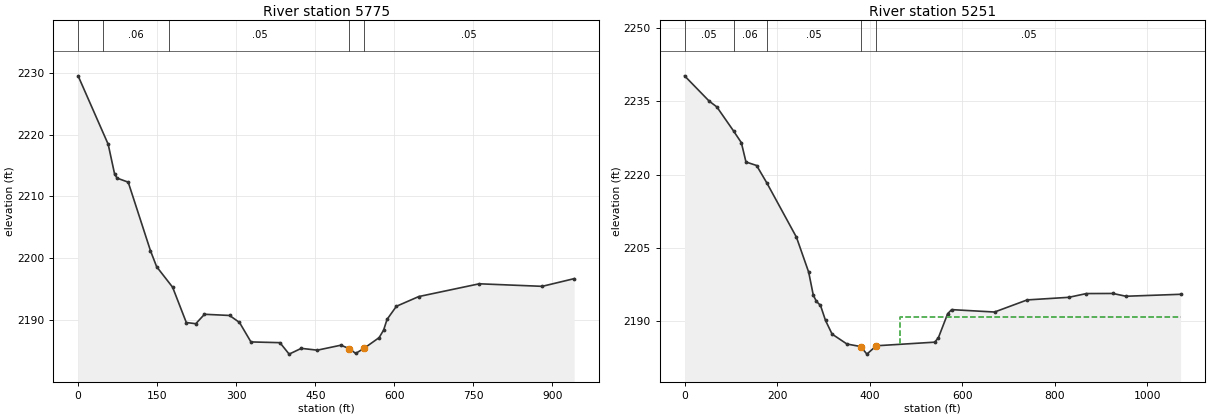
Type RM Length L Ch R = 1 ,5775    ,509.4,524.6,525.8
XS GIS Cut Line= 3
2114508.43854514359661.2978003922114192.50774655 359235.87115781
 2113864.0723798358988.466796979
#Sta/Elev= 30
       0 2229.47    57.1 2218.42    69.3 2213.61      74 2212.96    95.1 2212.31
   137.3 2201.25     149 2198.67   179.3 2195.36   205.3 2189.66   223.3 2189.47
   239.8 2190.99   287.4  2190.8   306.2 2189.67   327.9 2186.53   382.9 2186.41
   400.4 2184.56   423.4 2185.49   453.9  2185.2   498.5    2186  514.772185.442
   526.6 2184.67   542.4 2185.49   571.1 2187.22   579.7 2188.45   586.1 2190.16
   603.9 2192.28   646.3 2193.85   761.1 2195.91   880.5  2195.5   941.1 2196.74
#Mann= 5 ,-1 , 0
       0     .05       0   46.65     .06       0  173.09     .05       0
  514.77    .045       0   542.4     .05       0
Bank Sta=514.77,542.4
XS Rating Curve= 0 ,0
Exp/Cntr=0.3,0.1

Type RM Length L Ch R = 1 ,5251    ,165,159.6,150.6
XS GIS Cut Line= 4
2114628.76835696359632.1220057312114577.08374906359234.861973479
2114506.38408731359010.1350607282114177.91984922358723.912864149
#Sta/Elev= 30
       0 2240.22    53.2 2235.04    69.7 2233.86   105.8 2228.94   122.7 2226.54
   132.7 2222.58   155.7 2221.86   178.1 2218.24   241.8 2207.17   268.2 2200.02
   278.2  2195.3     285 2194.03   293.7 2193.22   304.6 2190.13   318.8 2187.34
   350.9 2185.31   380.7 2184.79     394 2183.24   414.3 2184.95   540.6 2185.69
   548.6 2186.62   568.6 2191.53   577.2 2192.35   669.8 2191.86   740.4 2194.34
   830.2 2194.87   868.4 2195.64   925.6 2195.66   953.7 2195.09  1071.9 2195.49
#Mann= 5 ,-1 , 0
       0     .05       0   105.8     .06       0   178.1     .05       0
   380.7    .045       0   414.3     .05       0
#XS Ineff= 2 , 0
                          465.39         2190.78
Permanent Ineff=
       F       F
Bank Sta=380.7,414.3
XS Rating Curve= 0 ,0
Exp/Cntr=0.5,0.3