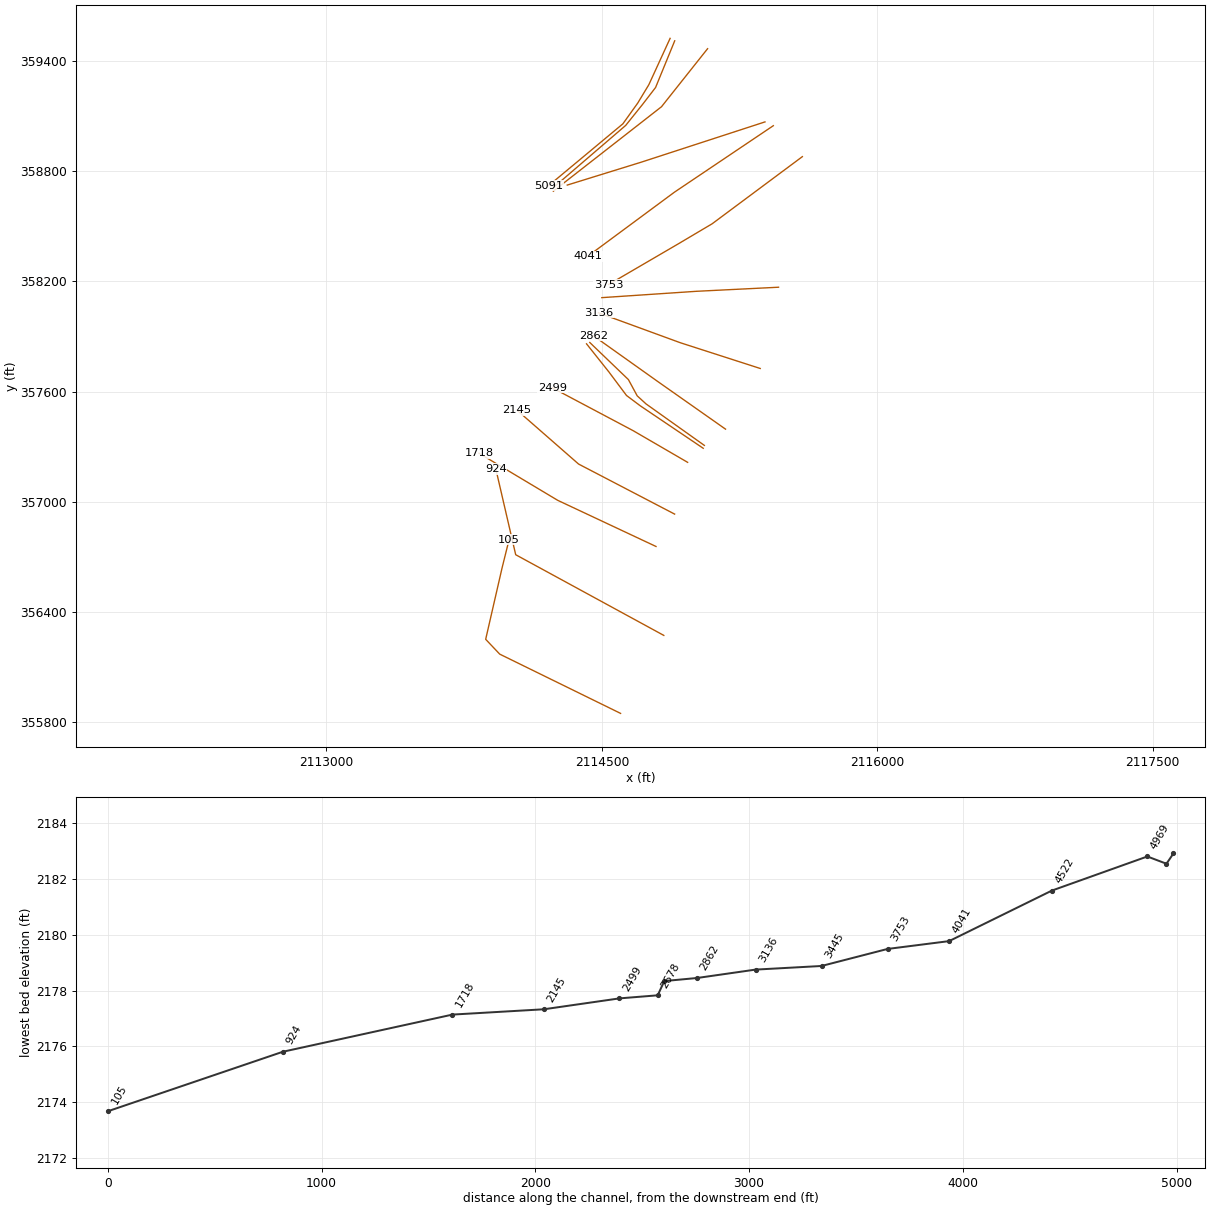
HEC-RAS study SNKNGCKT1.prj: SNKNGCKT1

--- SNKNGCKT1.g01 (geometry) --- (continued)

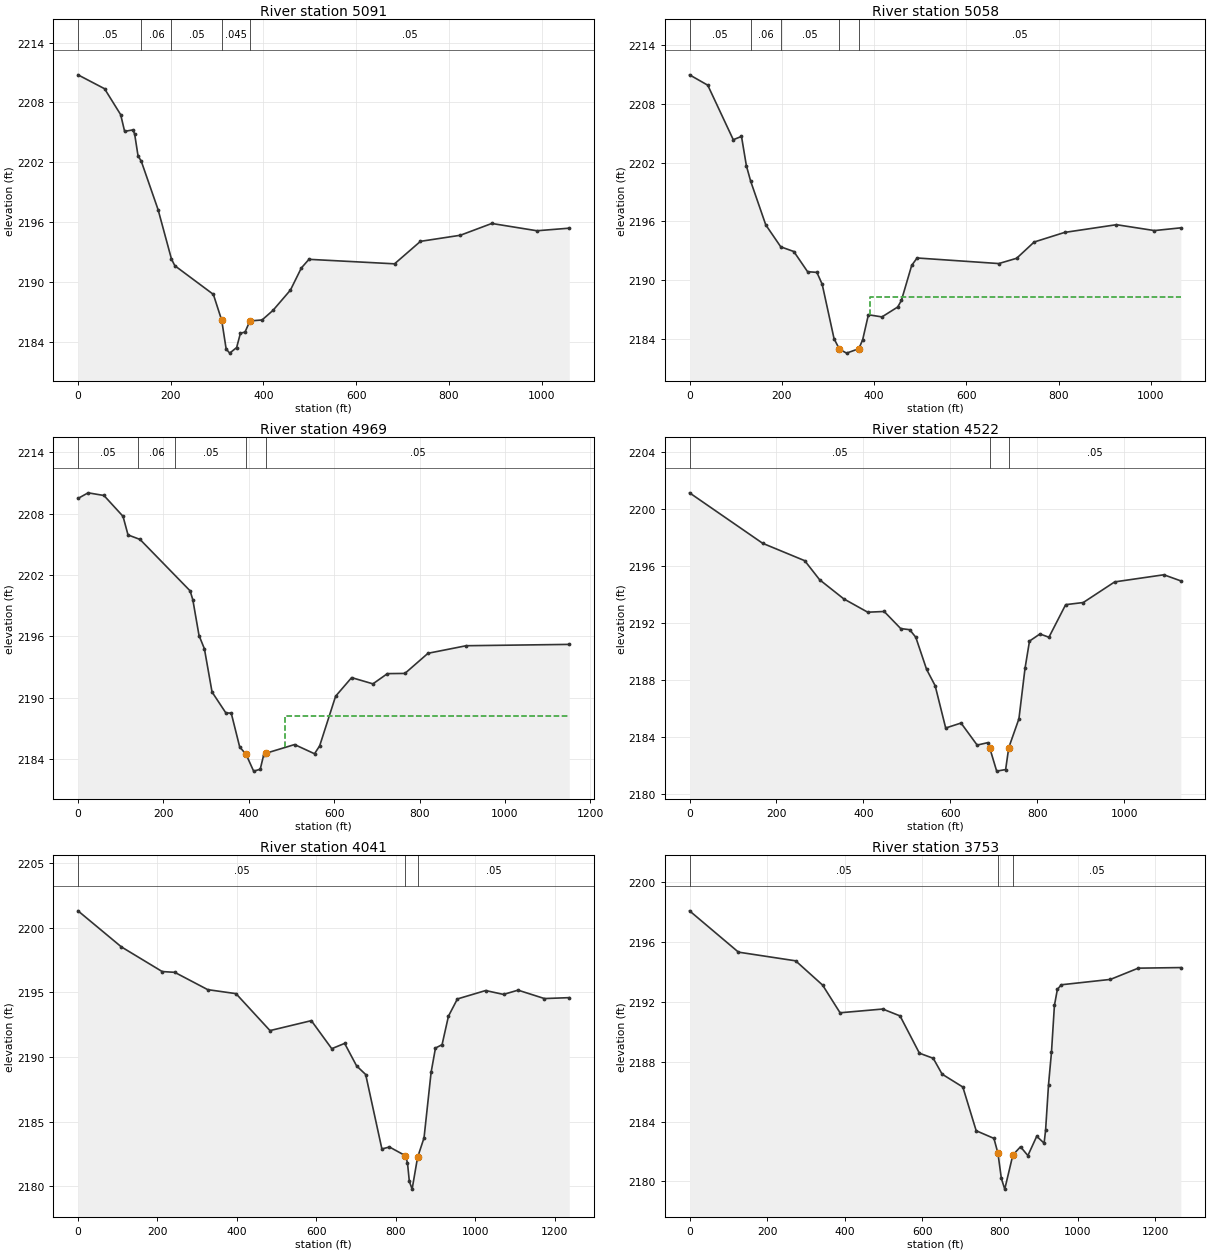
Type RM Length L Ch R = 1 ,5091    ,35.2,32.6,33.9
XS GIS Cut Line= 5
2114871.78460322359523.1904650632114756.15950638359271.106979728
2114695.74296056359171.1068516372114614.49279498359057.565412059
2114210.32628047 358721.10709548
#Sta/Elev= 30
       0 2210.77    57.3 2209.38    92.1 2206.78   100.6 2205.11   118.7 2205.26
   122.3 2204.82   129.5 2202.67   136.6 2202.11   172.8 2197.27   201.7 2192.32
   208.9 2191.66     292 2188.79  310.04 2186.19   319.6 2183.32   327.3 2182.91
   342.2 2183.47   350.3 2184.89   360.4 2185.03   370.8 2186.13   397.1 2186.23
   420.6 2187.19   458.2 2189.22   481.7 2191.43   498.2  2192.3   682.8 2191.85
   738.7  2194.1   824.7 2194.71   892.5 2195.89   989.9 2195.16  1059.7 2195.42
#Mann= 5 ,-1 , 0
       0     .05       0   136.6     .06       0   201.7     .05       0
  310.04    .045       0   370.8     .05       0
#XS Ineff= 2 ,-1
       0  302.02 2185.75  374.23     387 2185.75
Permanent Ineff=
       F       F
Bank Sta=310.04,370.8
XS Rating Curve= 0 ,0
Exp/Cntr=0.5,0.3

Type RM Length L Ch R = 1 ,5058    ,91.2,89.6,80.1
XS GIS Cut Line= 5
2114896.78455321359509.648497388 2114792.6177668359255.482010975
2114722.82623972359164.8568641392114630.11776373359049.232095391
2114230.11790755358705.482126728
#Sta/Elev= 30
       0 2210.97    39.5 2209.91    94.8 2204.34   112.6 2204.68   123.2 2201.68
   132.5  2200.1   165.2 2195.64   197.7  2193.4     226 2192.92   255.8 2190.86
     276 2190.79   287.5 2189.57   313.2 2184.01   324.9 2182.94   340.3 2182.54
   366.9 2182.99   375.2 2183.91   387.6 2186.46     417 2186.24   451.1 2187.25
   459.1 2187.92   481.4  2191.5   493.1 2192.26   670.2 2191.69   708.9 2192.23
   746.8 2193.89   812.7 2194.87   925.2 2195.66  1007.4 2195.06  1064.7 2195.34
#Mann= 5 ,-1 , 0
       0     .05       0   132.5     .06       0   197.7     .05       0
   324.9    .045       0   366.9     .05       0
#XS Ineff= 2 , 0
                          390.93         2188.29
Permanent Ineff=
       F       F
Bank Sta=324.9,366.9
XS Rating Curve= 0 ,0
Exp/Cntr=0.5,0.3

Type RM Length L Ch R = 1 ,4969    ,429,446.4,375
XS GIS Cut Line= 3
2115075.80912955359466.7680057292114824.92806964359150.830973566
2114235.90300097358691.031040147
#Sta/Elev= 30
       0 2209.48    23.8 2210.03    60.8 2209.77   105.5 2207.73   117.2 2205.91
   145.3 2205.47   262.6 2200.44     269 2199.56   283.5 2196.07   296.1 2194.77
     314 2190.54   346.4 2188.49   358.9 2188.48   378.7 2185.17  393.76 2184.43
   411.4  2182.8   426.8 2182.98   434.8 2184.36   441.1 2184.56   507.3  2185.4
     554  2184.5     566 2185.27   603.4 2190.13   640.9 2191.95   690.8 2191.34
   724.7 2192.34   765.7 2192.36   819.8 2194.33   909.3 2195.07  1150.7  2195.2
#Mann= 5 ,-1 , 0
       0     .05       0  140.01     .06       0  228.31     .05       0
  393.76    .045       0   441.1     .05       0
#XS Ineff= 2 , 0
                          485.44         2188.17
Permanent Ineff=
       F       F
Bank Sta=393.76,441.1
XS Rating Curve= 0 ,0
Exp/Cntr=0.3,0.1

Type RM Length L Ch R = 1 ,4522    ,476.8,481.1,468
XS GIS Cut Line= 3
 2115388.3961028359068.1165720672114715.19174056358849.022850141
2114311.71649763358724.157286227
#Sta/Elev= 30
       0 2201.14   168.4 2197.59     265 2196.37   299.3 2195.03   354.7 2193.69
   409.9 2192.75   447.8  2192.8   485.8  2191.6   506.5 2191.52   520.5 2190.99
   545.4 2188.73   565.1 2187.58   589.3 2184.61   624.6 2184.96   661.7 2183.41
   685.9 2183.58   690.9 2183.18   706.6 2181.58   727.2 2181.69   734.4 2183.23
   757.8 2185.26   771.8  2188.8   782.1 2190.72   806.2 2191.22   826.8 2190.99
   865.3 2193.28   905.8 2193.43   978.1 2194.88  1091.2 2195.38  1130.3 2194.95
#Mann= 3 ,-1 , 0
       0     .05       0   690.9    .045       0   734.4     .05       0
Bank Sta=690.9,734.4
XS Rating Curve= 0 ,0
Exp/Cntr=0.3,0.1

Type RM Length L Ch R = 1 ,4041    ,285.7,287.9,279.9
XS GIS Cut Line= 3
 2115433.7227838 359047.481442722114895.06014723358685.280395478
2114422.45544939358335.779125974
#Sta/Elev= 30
       0 2201.31   109.2 2198.52     212 2196.61   243.6 2196.55   326.6 2195.21
   397.8  2194.9   483.4 2192.04   587.5 2192.81   638.9 2190.64   671.3 2191.05
   701.4 2189.31   724.3 2188.64   765.1 2182.88   784.2 2183.03   824.12182.361
   829.5 2181.81   834.2 2180.37   841.2 2179.77   854.9 2182.22   871.2 2183.74
     889 2188.81     900 2190.69   916.6 2190.95   932.7 2193.16   955.2 2194.49
  1026.3 2195.14  1071.3 2194.84  1107.9 2195.17  1174.3 2194.52  1236.9 2194.59
#Mann= 3 ,-1 , 0
       0     .05       0   824.1    .045       0   854.9     .05       0
Bank Sta=824.1,854.9
XS Rating Curve= 0 ,0
Exp/Cntr=0.3,0.1

Type RM Length L Ch R = 1 ,3753    ,315.6,309,289.3
XS GIS Cut Line= 4
2115591.96656181358879.0004804732115100.74215056358513.421487227
2114921.52794205358407.1480777262114536.84564056358182.678710401
#Sta/Elev= 30
       0 2198.08   126.1 2195.32   273.4 2194.74   342.9 2193.12   387.9 2191.27
   497.9 2191.52   542.5 2191.06   592.4 2188.57     628 2188.23   650.9 2187.17
   704.3 2186.31   738.7 2183.39   784.4 2182.88   794.8 2181.88   803.5 2180.21
   812.3 2179.49   833.2 2181.77   852.9 2182.32   871.9 2181.73   894.7 2183.02
   913.7 2182.56   917.5 2183.41   925.1 2186.47   932.7 2188.63   940.3 2191.76
   947.9 2192.83   957.9 2193.14  1084.7  2193.5  1156.2 2194.25  1266.1 2194.29
#Mann= 3 ,-1 , 0
       0     .05       0   794.8    .045       0   833.2     .05       0
Bank Sta=794.8,833.2
XS Rating Curve= 0 ,0
Exp/Cntr=0.3,0.1

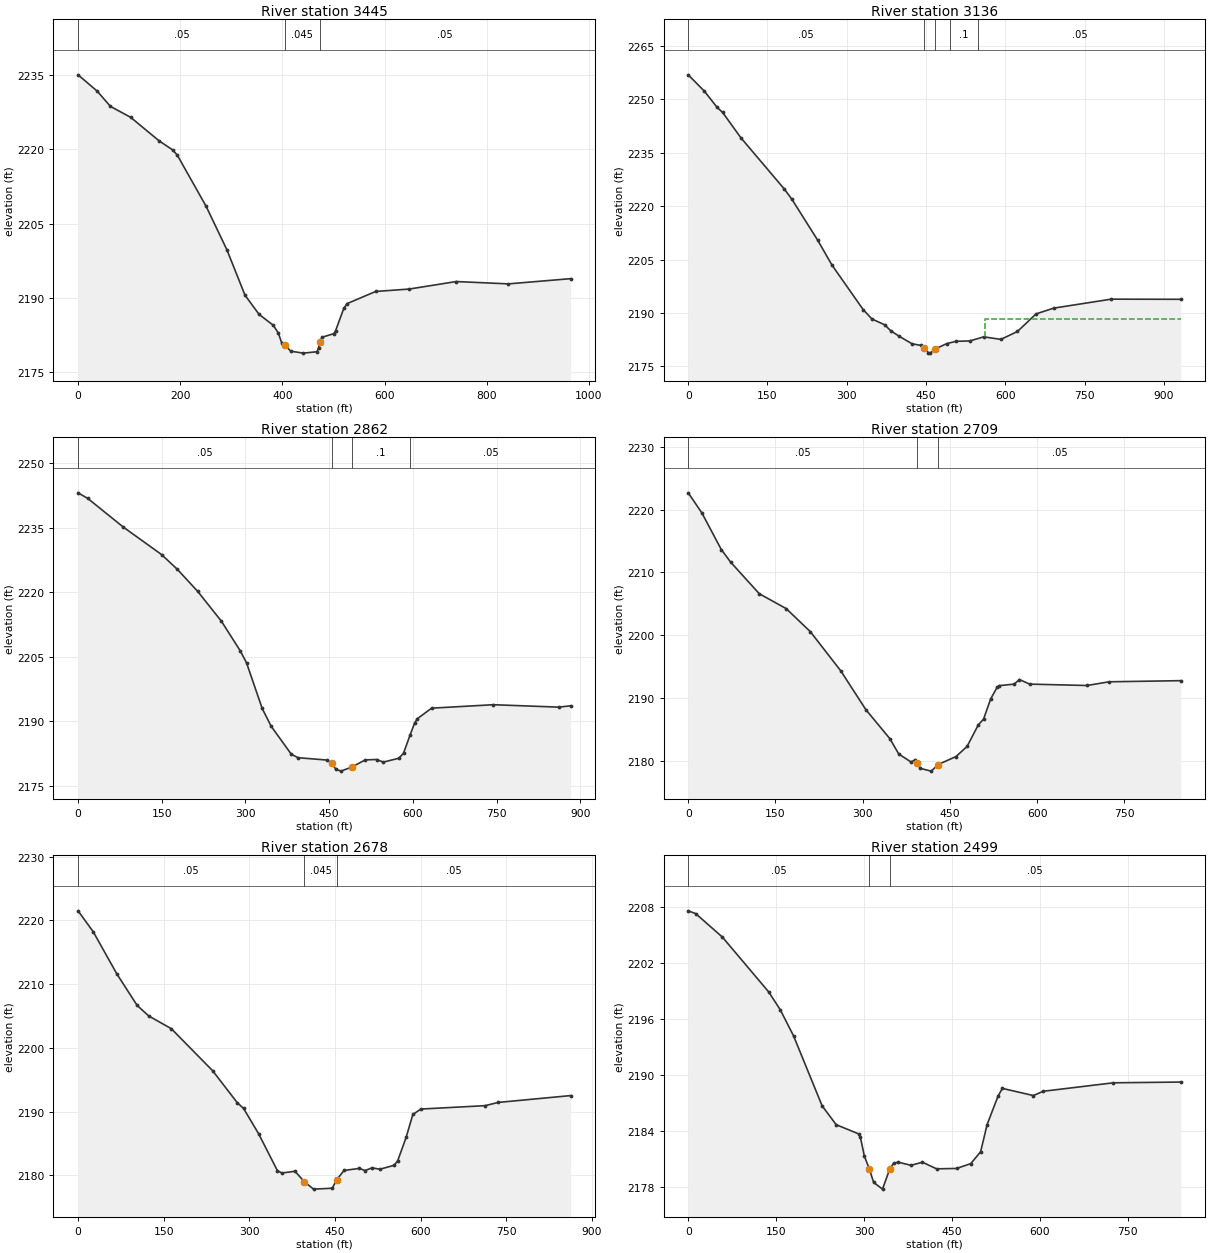
Type RM Length L Ch R = 1 ,3445    ,323.1,308.9,296.4
XS GIS Cut Line= 3
2115462.30409147358167.8841205542115016.11010197358145.743088722
2114499.83587205 358111.12603198
#Sta/Elev= 30
       0 2234.98    37.2 2231.72    63.5 2228.61   102.9 2226.42   158.7 2221.67
     185 2219.86   194.3 2218.79   250.8 2208.46   291.4 2199.71   326.8 2190.56
   354.4 2186.69   382.1  2184.5     392 2182.96   398.5 2180.98   405.1 2180.47
   416.5 2179.27   440.9 2178.88   467.5 2179.16   470.8 2179.91  473.122181.042
   477.4 2182.07   500.7 2182.81   504.2  2183.4   520.1 2187.88   526.7 2188.86
   582.6 2191.31   648.4  2191.8   740.3 2193.31   842.4 2192.84   964.2 2193.89
#Mann= 3 ,-1 , 0
       0     .05       0   405.1    .045       0  473.12     .05       0
Bank Sta=405.1,473.12
XS Rating Curve= 0 ,0
Exp/Cntr=0.3,0.1

Type RM Length L Ch R = 1 ,3136    ,270.7,273.2,265.4
XS GIS Cut Line= 3
2115362.44799197357725.464073643 2114927.1470253357865.666877225
2114481.27193281358028.709858224
#Sta/Elev= 30
       0 2256.82    30.6 2252.23    54.8 2247.67    65.1 2246.28    99.6 2239.17
   182.1 2224.74   196.1 2221.93     245 2210.43   271.9 2203.48     331 2190.97
   347.7 2188.32   371.9 2186.69   383.1 2185.04   399.4 2183.47   423.6 2181.37
   440.8 2180.91  446.332180.297   454.6 2178.81     458 2178.75  466.532179.845
   489.5 2181.44   506.9 2182.06   532.9 2182.17   559.3 2183.32   591.7  2182.6
     623 2184.83   658.2 2189.75   691.5 2191.37   800.4 2193.89   932.1 2193.85
#Mann= 5 ,-1 , 0
       0     .05       0  446.33    .045       0  466.53     .05       0
  495.67      .1       0   548.5     .05       0
#XS Ineff= 2 , 0
                          561.97         2188.39
Permanent Ineff=
       F       F
Bank Sta=446.33,466.53
XS Rating Curve= 0 ,0
Exp/Cntr=0.3,0.1

Type RM Length L Ch R = 1 ,2862    ,151.4,153.5,147.6
XS GIS Cut Line= 3
2115173.50315988357395.0900624842114807.34149064357652.415007144
2114452.89797381357904.463715643
#Sta/Elev= 30
       0 2243.11    17.2 2241.83    81.4 2235.12   149.6 2228.77   177.6 2225.38
   214.5  2220.2   256.9 2213.27   290.4 2206.45   301.9  2203.6   329.9 2193.02
     346 2188.88   382.1 2182.37   394.2 2181.57   446.3 2181.02   454.7 2180.27
   461.7  2178.9   471.1 2178.45   490.6 2179.42   514.7 2181.06   534.9 2181.15
   546.9 2180.55   574.7 2181.44   583.2 2182.62   595.2 2186.95   602.9 2189.58
   607.6  2190.6   633.5 2193.08   743.8 2193.88   860.9 2193.32   882.5 2193.62
#Mann= 4 ,-1 , 0
       0     .05       0   454.7    .045       0   490.6      .1       0
   595.2     .05       0
Bank Sta=454.7,490.6
XS Rating Curve= 0 ,0
Exp/Cntr=0.5,0.3

Type RM Length L Ch R = 1 ,2709    ,26.9,30.9,36
XS GIS Cut Line= 5
2115058.24289171357306.5236385612114740.53453764357532.565181226
 2114692.6179668357576.3154218052114644.70106789357664.856911391
2114434.28449397357866.940168649
#Sta/Elev= 30
       0 2222.67    23.4 2219.48      57 2213.62    72.8 2211.65   122.2  2206.6
   168.5 2204.23     210 2200.56   262.4 2194.31   305.7 2188.11   346.9  2183.5
   362.1 2181.07   383.3 2179.79   389.9 2180.13   394.2 2179.59     399 2178.78
     418 2178.34   429.9 2179.39   460.5 2180.66   479.6 2182.27     499 2185.72
     508 2186.63   520.2 2189.84   531.4 2191.71   535.3 2191.96   560.6  2192.2
   569.7 2192.93   587.2  2192.2     686 2191.98   723.8 2192.57   847.2 2192.75
#Mann= 3 ,-1 , 0
       0     .05       0   394.2    .045       0   429.9     .05       0
#XS Ineff= 2 , 0
           384.8  2179.8   439.9          2179.8
Permanent Ineff=
       F       F
Bank Sta=394.2,429.9
XS Rating Curve= 0 ,0
Exp/Cntr=0.5,0.3

Type RM Length L Ch R = 1 ,2678    ,165.1,178.8,183.6
XS GIS Cut Line= 5
2115051.99290422357290.8986698092114709.28460014357522.148535401
2114634.28442205357578.3987509762114538.45128039 357706.52349472
2114416.57619606357859.648516566
#Sta/Elev= 30
       0 2221.48    26.6  2218.2      68 2211.58   103.5 2206.65   123.7    2205
   163.3    2203   235.8  2196.4   278.8  2191.4     290 2190.48   316.2 2186.54
   349.3 2180.72   357.2 2180.36     380 2180.63   396.5 2178.99   412.6 2177.83
   445.4 2177.97   452.9 2179.26   465.9 2180.76   492.8 2181.08   502.8 2180.75
     515 2181.17   528.8 2180.95   553.7 2181.57     560 2182.28   574.8 2185.96
   586.5 2189.54   600.6 2190.39   712.9 2190.92   736.2 2191.43   862.9  2192.5
#Mann= 3 ,-1 , 0
       0     .05       0   396.5    .045       0   452.9     .05       0
Bank Sta=396.5,452.9
XS Rating Curve= 0 ,0
Exp/Cntr=0.5,0.3

Type RM Length L Ch R = 1 ,2499    ,354.8,353.8,350.5
XS GIS Cut Line= 3
 2114967.0800163357214.400791317 2114669.8148628357387.107138813
2114231.07394239357619.662119895
#Sta/Elev= 30
       0 2207.61    12.8 2207.31    58.3 2204.79   137.3  2198.9     157 2196.99
   179.8 2194.17   228.5 2186.66   252.5 2184.64   290.9 2183.65   293.6 2183.34
   300.5 2181.28   308.8 2179.92   316.4 2178.44   331.5 2177.72   343.8 2179.88
   350.4 2180.49   357.8 2180.62   380.1 2180.28   399.6 2180.61   423.8  2179.9
   457.8 2179.94   482.1 2180.46   498.9 2181.74     510 2184.66   528.6 2187.71
     536 2188.54   588.9 2187.77   605.8 2188.23   725.4 2189.14   840.4 2189.22
#Mann= 3 ,-1 , 0
       0     .05       0   308.8    .045       0   343.8     .05       0
Bank Sta=308.8,343.8
XS Rating Curve= 0 ,0
Exp/Cntr=0.3,0.1

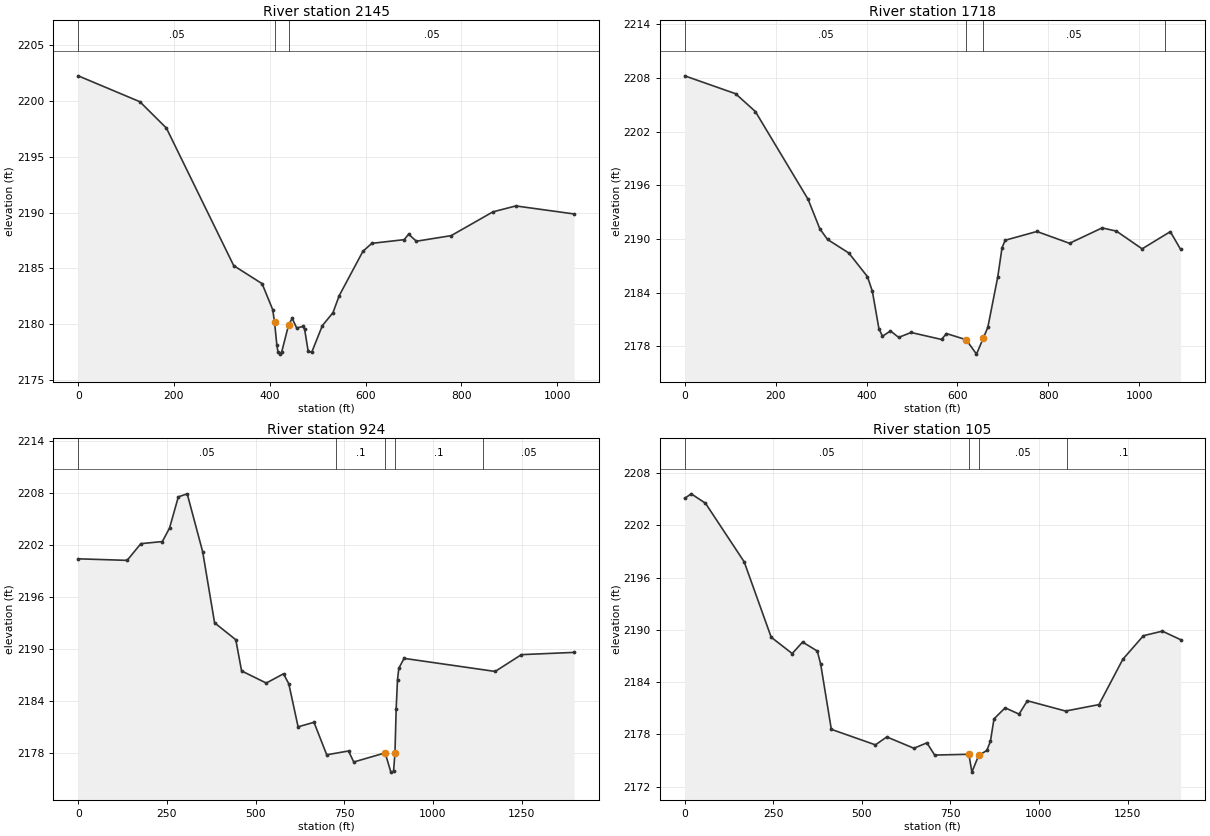
Type RM Length L Ch R = 1 ,2145    ,385.3,427.6,403.3
XS GIS Cut Line= 3
2114896.29538096356932.4971556372114373.25771314357205.040573806
2114037.62551039357498.623976141
#Sta/Elev= 30
       0 2202.25   128.8 2199.93   184.2 2197.57   324.8 2185.25     384 2183.64
   406.2 2181.31     410  2180.2   414.9 2178.12   417.3  2177.5     421 2177.33
   425.1 2177.55   439.5 2179.97   446.9 2180.54   456.2 2179.67   469.1 2179.81
   472.8 2179.56   480.2  2177.6   487.6 2177.49   509.8 2179.88     532 2181.04
   545.1 2182.57   594.6 2186.54   613.2 2187.25   680.7 2187.58     690 2188.07
   706.2 2187.44   778.9 2187.94   866.1 2190.07     914  2190.6  1035.7 2189.88
#Mann= 3 ,-1 , 0
       0     .05       0     410    .045       0   439.5     .05       0
Bank Sta=410,439.5
XS Rating Curve= 0 ,0
Exp/Cntr=0.3,0.1

Type RM Length L Ch R = 1 ,1718    ,743.4,793.4,742.9
XS GIS Cut Line= 3
2114794.87596439356756.1769702292114259.86981656357007.353305146
2113830.85295805357263.959419221
#Sta/Elev= 30
       0 2208.25     112 2206.25   155.5 2204.26   271.4 2194.45   297.3 2191.15
   314.2 2189.96   361.1 2188.44   401.9 2185.81   412.8 2184.18   427.3 2179.98
   435.1 2179.14   452.7 2179.73   470.8 2179.01     498 2179.56     565 2178.78
   575.9 2179.44   619.2 2178.75   641.9 2177.14  656.622178.904   666.8 2180.13
   688.6 2185.75   698.1 2189.04     705 2189.87   774.7 2190.85   846.5 2189.53
   918.2 2191.25   949.7 2190.89  1006.2 2188.91  1068.2 2190.83  1090.9 2188.85
#Mann= 4 ,-1 , 0
       0     .05       0   619.2    .045       0  656.62     .05       0
 1057.25      .1       0
Bank Sta=619.2,656.62
XS Rating Curve= 0 ,0
Exp/Cntr=0.3,0.1

Type RM Length L Ch R = 1 ,924     ,777.1,818.9,760.9
XS GIS Cut Line= 3
2114837.52646963356271.8423089832114030.89750548356711.243004978
2113922.63951989357178.238462061
#Sta/Elev= 30
       0 2200.43   137.9 2200.25   176.6 2202.18   237.1 2202.42   257.4 2203.98
   282.2 2207.58   307.2 2207.93   350.8 2201.25   384.4 2193.04   444.2 2191.09
   460.5 2187.49   530.1 2186.09   578.7 2187.16   593.6    2186   619.8 2181.04
   664.6 2181.56   700.5 2177.81   761.9 2178.25   776.7 2176.98   865.1 2178.03
   881.3 2175.81   888.8 2175.89  892.872178.052   896.2 2183.11     900 2186.49
   903.7  2187.8   918.5 2188.94  1175.2 2187.43  1249.3 2189.37  1397.9 2189.63
#Mann= 5 ,-1 , 0
       0     .05       0  727.44      .1       0   865.1    .045       0
  892.87      .1       0  1142.2     .05       0
Bank Sta=865.1,892.87
XS Rating Curve= 0 ,0
Exp/Cntr=0.3,0.1

Type RM Length L Ch R = 1 ,105     ,98.4,105.42,112.5
XS GIS Cut Line= 6
2114601.90587789355847.3008352222113943.86651155 356169.95242089
2113867.44901347356250.6153173152113956.60270655356639.070905223
2113989.11962074356769.5813262822113990.92124302356792.120237598
#Sta/Elev= 30
       0  2205.1    18.5 2205.62    58.7 2204.54     168 2197.81   244.2 2189.16
   303.5 2187.29   332.8 2188.61   374.2 2187.58   383.8 2186.08   413.9 2178.59
   538.4 2176.81   570.4 2177.72     647 2176.42   683.6 2177.04   705.5 2175.64
   802.1 2175.73   810.6 2173.68   829.7 2175.59   852.8 2176.17   862.9 2177.22
     873 2179.79   904.4 2181.06   943.7 2180.34   967.2 2181.87  1075.1 2180.69
  1169.2 2181.43  1236.6 2186.63  1294.8 2189.34  1348.1 2189.86  1399.7 2188.88
#Mann= 4 ,-1 , 0
       0     .05       0   802.1    .045       0   829.7     .05       0
 1079.48      .1       0
Bank Sta=802.1,829.7
XS Rating Curve= 0 ,0
Exp/Cntr=0.3,0.1
LCMann Table=0

Chan Stop Cuts=-1
Use User Specified Reach Order=0
Composite Channel Slope=5